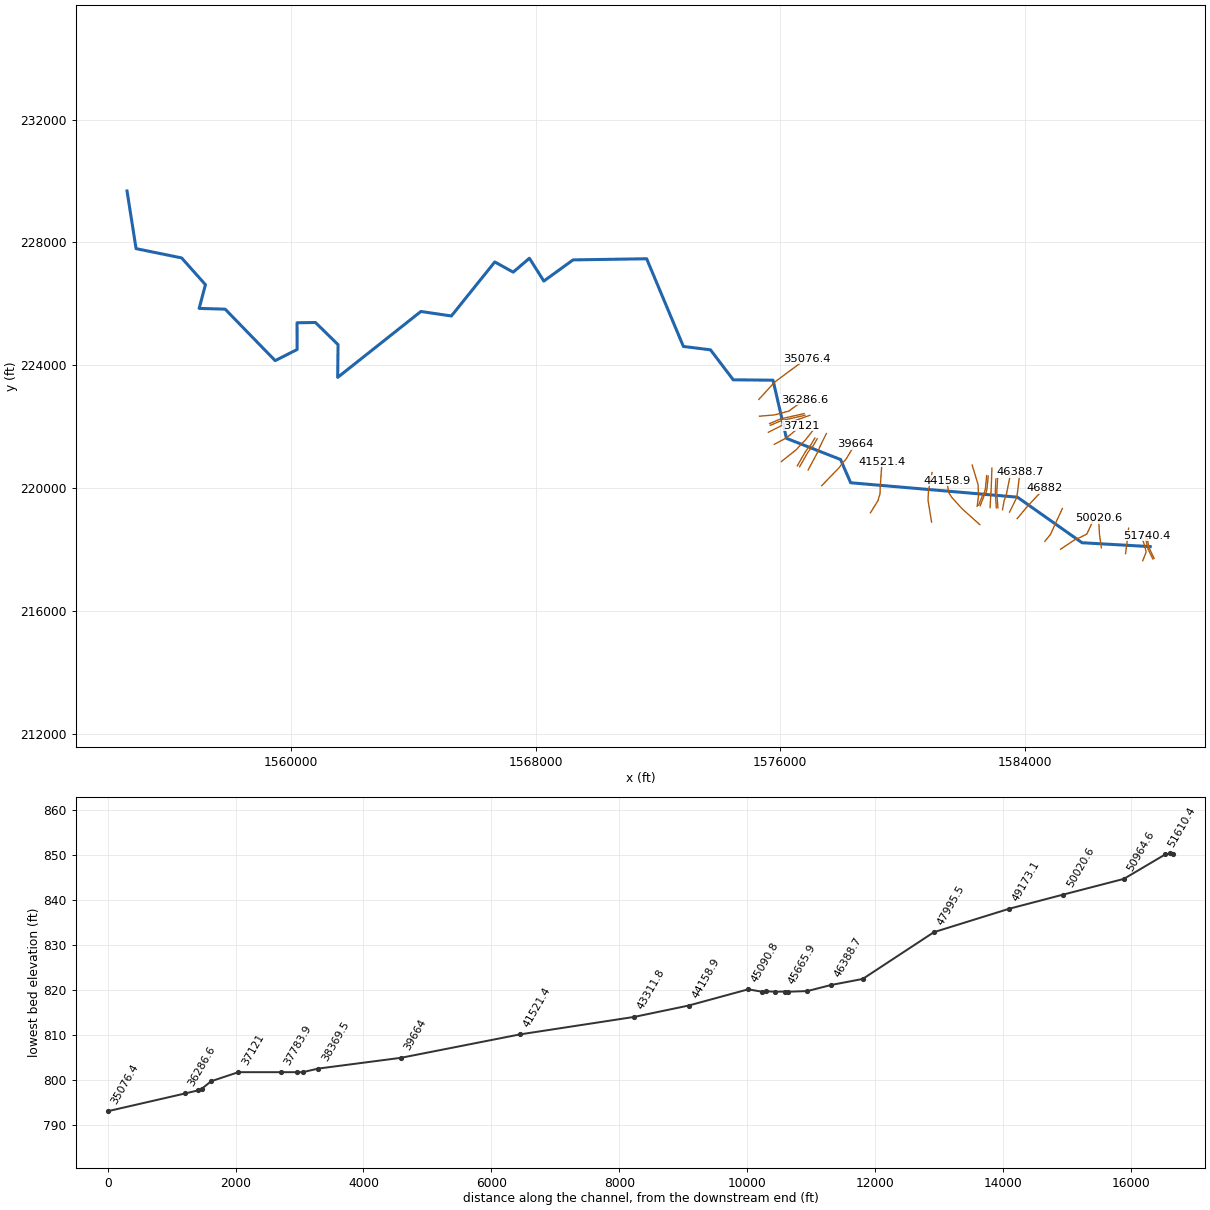
--- BNCR.prj (project) ---

Proj Title=BNCR
Current Plan=p01
Default Exp/Contr=0,0
English Units
Geom File=g01
Flow File=f01
Plan File=p01
BEGIN DESCRIPTION:
END DESCRIPTION:
DSS Export Rating Curves= 0
DSS Export Rating Curve Sorted= 0
DSS Export Volume Flow Curves= 0
DXF OffsetX= 0
DXF OffsetY= 0
DXF ScaleX= 0
DXF ScaleY= 0

--- BNCR.p01 (plan) ---

Plan Title=Floodplain
Program Version=4.00
Geom File=g01
Flow File=f01
K Sum by GR=0
Std Step Tol=0.01
Critical Tol=0.01
Num of Std Step Trials=20
Max Error Tol=0.3
Flow Tol Ratio=0.001
Split Flow NTrial=30
Split Flow Tol=0.02
Split Flow Ratio=0.02
Log Output Level=0
Friction Slope Method=1
Unsteady Friction Slope Method=2
Unsteady Bridges Friction Slope Method=1
Global Log Level=0
CheckData=False
Run HTab=0
Run UNet=0
Run PostProcess=0
UNET Theta=0
UNET Theta Warmup=0
UNET ZTol=0
UNET ZSATol=0
UNET MxIter=0
UNET MaxInSteps=0
UNET DtIC=0
UNET DtMin=0
UNET MaxCRTS=0
UNET WFStab=0
UNET SFStab=0
UNET WFX=0
UNET SFX=0
UNET DSS MLevel=0
UNET DZMax Abort=0
UNET Convert EG Bridges=0
UNET Use Existing IB Tables=0
UNET Froude Limit=0
UNET Froude Power=0
Write IC File=0
Echo Input=False
Echo Output=False
Write Detailed=0

--- BNCR.f01 (steady flow) ---

Flow Title=NFF Regression Equation
Program Version=4.10
Number of Profiles= 1
Profile Names=P100yr
River Rch & RM=BNCR,Main            ,51740.4
890.6373
River Rch & RM=BNCR,Main            ,50020.6
926.7655
River Rch & RM=BNCR,Main            ,49173.1
979.0861
River Rch & RM=BNCR,Main            ,46882
1041.582
River Rch & RM=BNCR,Main            ,46388.7
1848.771
River Rch & RM=BNCR,Main            ,44158.9
1887.784
River Rch & RM=BNCR,Main            ,43311.8
2200.273
River Rch & RM=BNCR,Main            ,38369.5
2350.003
River Rch & RM=BNCR,Main            ,37783.9
2389.728
River Rch & RM=BNCR,Main            ,35076.4
2544.337
River Rch & RM=BNCR,Main            ,33416.1
2897.254
River Rch & RM=BNCR,Main            ,29718.5
3055.349
River Rch & RM=BNCR,Main            ,27915
3136.432
River Rch & RM=BNCR,Main            ,22902.8
3259.379
River Rch & RM=BNCR,Main            ,21358.5
3388.504
River Rch & RM=BNCR,Main            ,15885.4
3500.134
River Rch & RM=BNCR,Main            ,15452.4
3751.919
River Rch & RM=BNCR,Main            ,6692.5
3887.021
River Rch & RM=BNCR,Main            ,5060.9
4004.405
River Rch & RM=BNCR,Main            ,560.4
4071.248
Boundary for River Rch & Prof#=BNCR,Main            , 1
Up Type= 0
Dn Type= 3
Dn Slope=0.00117
DSS Import GetInterval= 0
DSS Import GetPeak= 0
DSS Import FillOption= 0

--- BNCR.g01 (geometry) ---

Geom Title=USGS 10m DEM
Program Version=4.10

River Reach=BNCR            ,Main
Reach XY= 30
     1588105.252      218099.944     1585875.868      218225.946
     1583761.017       219709.46     1578307.484      220178.304
     1577976.181      220936.092     1576206.708      221624.531
     1575767.751      223517.647     1574466.482      223529.544
     1573723.226      224505.446     1572836.248      224615.413
     1571633.991       227470.23     1569227.307      227433.338
     1568270.276      226744.319     1567799.356      227487.592
     1567268.757      227035.118     1566667.628      227367.149
     1565246.491       225607.21     1564249.964      225754.432
      1561527.59      223608.202     1561539.999      224674.513
      1560801.67      225395.099     1560198.656      225386.431
     1560201.606      224516.201     1559483.398      224154.375
     1557847.008      225829.625     1556996.486      225854.334
     1557203.039      226626.134     1556423.708      227497.583
     1554933.669      227799.628     1554637.224       229676.61

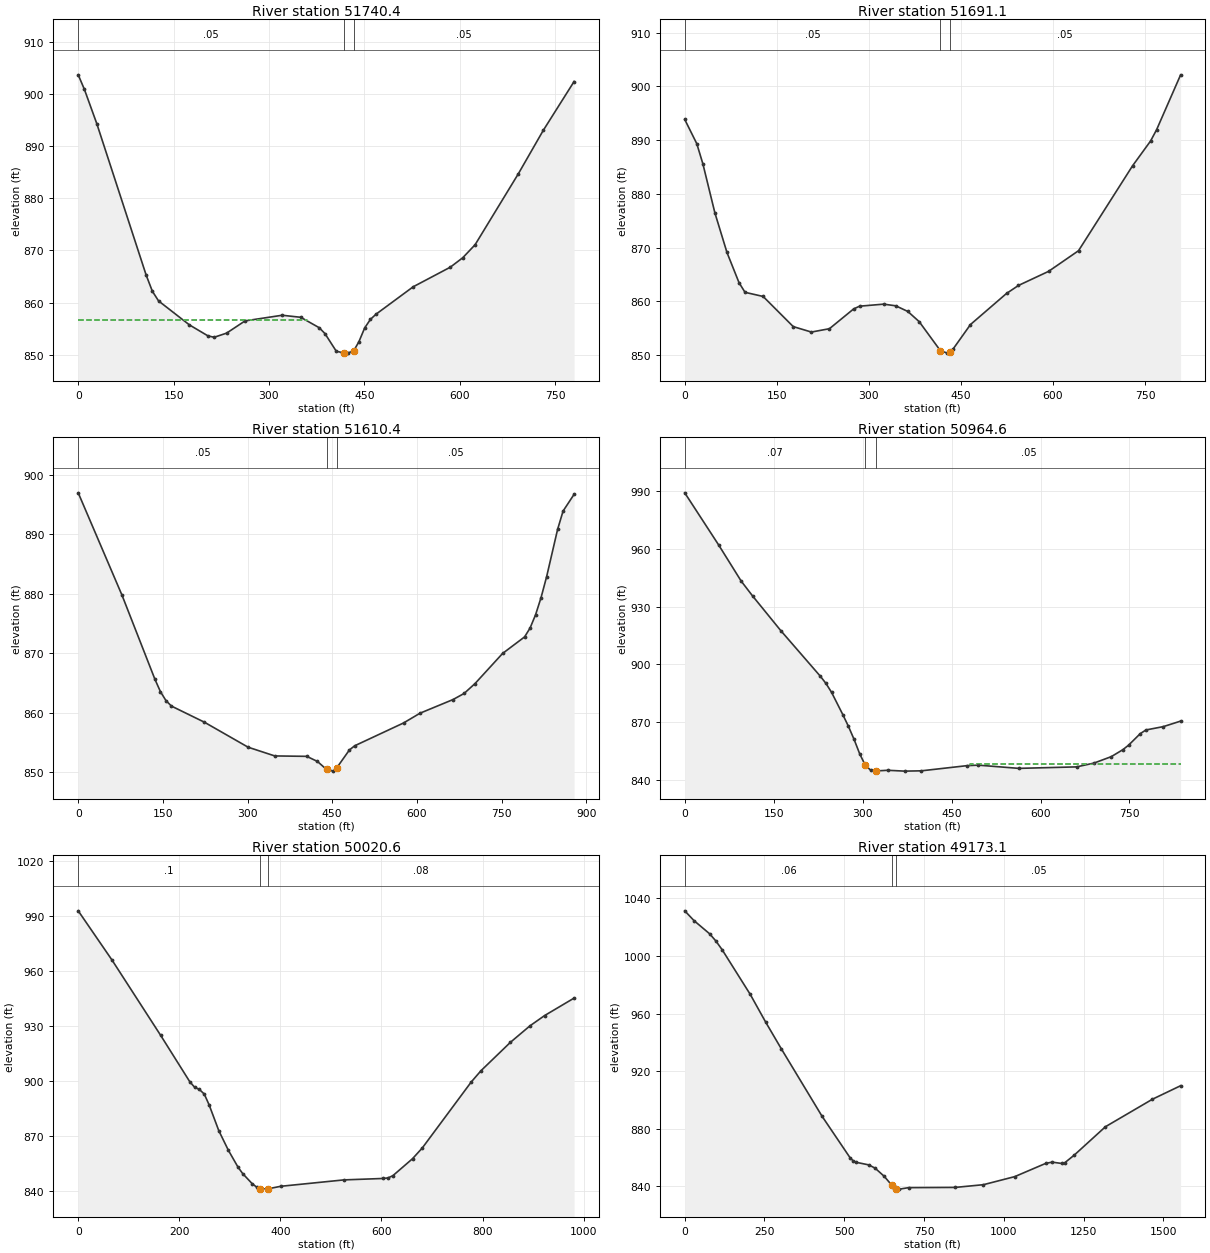
Type RM Length L Ch R = 1 ,51740.4 ,48.1,49.3,50.7
XS GIS Cut Line= 4
     1588231.554      217714.961     1588071.832      218058.711
     1588050.998      218145.517     1587990.234      218451.072
#Sta/Elev= 30
       0  903.64     9.7  900.86    29.2  894.29   106.9  865.24   116.6  862.16
   126.4   860.3   174.9  855.71   204.1   853.6   213.8  853.34   233.3  854.13
   262.4  856.48   320.7  857.56   349.9  857.17     379  855.17     388  854.05
   405.8  850.67   418.3  850.31   423.7   850.3   433.3  850.75   441.5  852.51
   450.5  855.13   459.4  856.75   468.3  857.76   526.7  863.01   585.1  866.77
   604.6  868.57   624.1  871.07   692.2  884.69   731.2  892.97   779.8  902.36
#Mann= 3 , 0 , 0
       0     .05       0   418.3     .04       0   433.3     .05       0
#XS Ineff= 2 , 0
          359.87  856.62
Permanent Ineff=
       F       F
Bank Sta=418.3,433.3
XS Rating Curve= 0 ,0
Exp/Cntr=0.3,0.1

Type RM Length L Ch R = 1 ,51691.1 ,81.8,80.7,79.4
XS GIS Cut Line= 4
     1588189.887        217697.6     1588033.637      218025.725
     1588007.595      218114.267     1587939.887      218459.753
#Sta/Elev= 30
       0  893.83    19.6  889.33    29.5   885.6    49.1  876.46    68.8  869.09
    88.4  863.48    98.2  861.68   127.7  860.91   176.8   855.3   206.3  854.29
   235.7  854.91     275  858.58   284.8   859.1   324.1  859.48   343.8  859.17
   363.4  858.12   381.9  856.23   416.5  850.82     428  850.37   431.5  850.67
   437.3  851.16   465.5  855.69   524.2  861.47   543.7  862.96   592.6  865.57
   641.5  869.42   729.5  885.21   758.9  889.83   768.7  891.93   807.8  902.13
#Mann= 3 , 0 , 0
       0     .05       0   416.5     .04       0   431.5     .05       0
Bank Sta=416.5,431.5
XS Rating Curve= 0 ,0
Exp/Cntr=0.3,0.1

Type RM Length L Ch R = 1 ,51610.4 ,653.6,645.8,635.9
XS GIS Cut Line= 4
     1587861.762      217640.308     1587972.439      217920.256
     1587920.356      218140.742     1587808.806      218473.464
#Sta/Elev= 30
       0  897.01    77.7  879.74     136  865.58   145.7  863.51   155.4  862.02
   165.1  861.09   223.4  858.38     301  854.16   348.2  852.69   404.9  852.62
   423.8  851.76  440.06850.4064   452.1  850.13     458  850.68   480.4  853.69
   489.8   854.4   576.3  858.24   605.6  859.89   664.1  862.19   683.6  863.21
     703  864.88   751.8  869.95   790.8  872.74   800.5  874.23   810.3  876.48
     820  879.37   829.8  882.87   849.3  890.86     859  893.94   878.5  896.76
#Mann= 3 , 0 , 0
       0     .05       0  440.06     .04       0     458     .05       0
Bank Sta=440.06,458
XS Rating Curve= 0 ,0
Exp/Cntr=0.3,0.1

Type RM Length L Ch R = 1 ,50964.6 ,937.8,944,949.1
XS GIS Cut Line= 4
     1587299.034      217870.861     1587327.612      218097.802
     1587358.051      218323.037     1587399.523      218701.072
#Sta/Elev= 30
       0  988.97    57.2  961.94    95.3  943.16   114.4  935.52     162  917.53
   228.7  893.89   238.2  890.14   247.7   885.5   266.6  873.99   276.1  867.89
   285.6  861.15     295  853.72   304.4  847.79     314  845.06   323.4  844.81
   342.4  845.14   370.8   844.7   399.2  844.86   475.5  847.52     495   847.8
   563.3  846.13   660.8   846.9     690  848.85   719.3   852.2   738.8   855.8
   748.6  858.17   768.1   864.1   777.8  866.04   807.1  867.77   836.3  870.63
#Mann= 3 , 0 , 0
       0     .07       0   304.4    .045       0   323.4     .05       0
#XS Ineff= 2 , 0
                          480.69           848.2
Permanent Ineff=
       F       F
Bank Sta=304.4,323.4
XS Rating Curve= 0 ,0
Exp/Cntr=0.3,0.1

Type RM Length L Ch R = 1 ,50020.6 ,876.6,847.5,815.4
XS GIS Cut Line= 4
     1586509.332      218057.843     1586467.665      218342.565
     1586446.832      218491.871     1586415.582      219033.538
#Sta/Elev= 30
       0   992.9    67.1  965.98   163.1  925.04   220.6  899.82   230.2  896.77
   239.8  895.53   249.4  893.04     259  887.15   278.2  873.05   297.2  862.34
     316  853.28   325.4  849.69   344.3  844.16   353.7  842.18     360  841.54
   372.6  841.22     375  841.36   400.8  842.77   525.7  846.25   603.2  847.03
   612.9  847.32   622.6  848.56   661.4  857.79   680.7  863.64   777.6  899.62
     797  905.79   855.1  921.23   893.9  930.24   922.9  935.84   981.1  945.34
#Mann= 3 , 0 , 0
       0      .1       0     360    .045       0     375     .08       0
Bank Sta=360,375
XS Rating Curve= 0 ,0
Exp/Cntr=0.3,0.1

Type RM Length L Ch R = 1 ,49173.1 ,1157.3,1177.6,1193.4
XS GIS Cut Line= 5
     1585173.864      218015.612     1585670.826      218345.473
     1585805.375      218395.387     1586033.637      218509.232
     1586269.748      219016.176
#Sta/Elev= 30
       0 1031.39    29.3 1024.54    78.2  1015.4    97.8 1010.38   117.3 1004.36
   205.3  973.35   254.2  953.87   303.1  935.39   430.2  888.75   518.2  859.87
     528  857.71   537.8  856.68   576.9  854.89   596.5  852.66   625.2  846.97
  649.69840.5962   663.4  838.31     673  838.06   701.7  839.09   847.9  839.25
   936.2  841.14  1034.3  846.74  1132.4  856.03    1152   856.8  1181.5  855.89
  1191.3  856.41  1220.7  861.65  1318.8  881.43    1466  900.52  1554.3   909.9
#Mann= 3 , 0 , 0
       0     .06       0  649.69    .045       0   663.4     .05       0
Bank Sta=649.69,663.4
XS Rating Curve= 0 ,0
Exp/Cntr=0.3,0.1

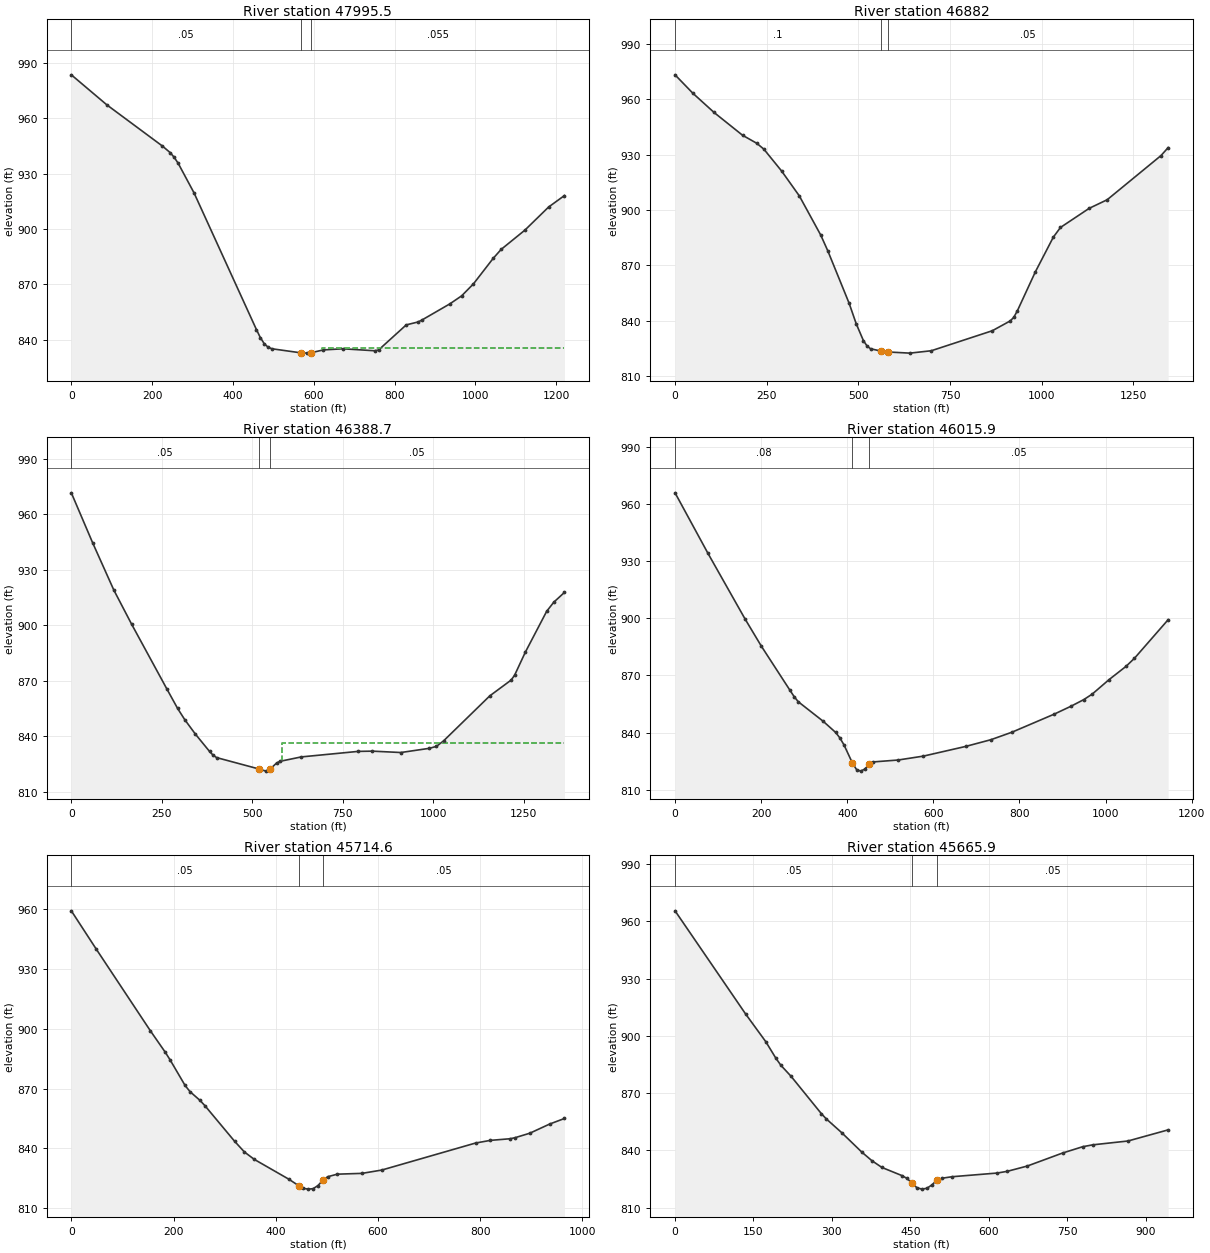
Type RM Length L Ch R = 1 ,47995.5 ,1119.5,1113.5,1105.5
XS GIS Cut Line= 4
     1584658.637      218269.649     1584849.609       218505.76
     1584943.359      218717.565     1585231.554      219339.093
#Sta/Elev= 30
       0  983.37    88.2  967.08   225.3  944.87   244.9  941.25   254.7  938.71
   264.5   935.5   303.7  919.52   458.1   845.6   467.7  841.29   477.4  837.96
     487  836.04   496.7   835.2  569.05832.9797   584.2  832.85     594  833.09
   623.4  834.58   672.3   835.2   750.6  834.13   760.4  834.56   828.9  848.13
   858.3  849.71   868.1  850.81   936.6  859.47   965.9  863.82   995.3  870.34
  1044.2  884.15  1063.8  888.96  1122.5  899.37  1181.2  911.87  1220.4  918.08
#Mann= 3 , 0 , 0
       0     .05       0  569.05    .045       0     594    .055       0
#XS Ineff= 2 , 0
                          621.01          835.49
Permanent Ineff=
       F       F
Bank Sta=569.05,594
XS Rating Curve= 0 ,0
Exp/Cntr=0.3,0.1

Type RM Length L Ch R = 1 ,46882   ,483.5,493.4,503.3
XS GIS Cut Line= 4
     1583754.991      219010.968     1584033.637      219346.038
     1584203.776      219533.538     1584655.165      220009.232
#Sta/Elev= 30
       0  973.38    48.4  963.43   106.5  952.95     184  940.62   222.7  936.27
   242.1  933.09   290.5  921.24     339  907.69   397.1  886.55   416.4  878.01
   474.7   849.5   494.2  838.29   513.7  829.23   523.4  826.37   533.2   824.8
   561.5  823.57   581.9  823.05   640.3  822.44   698.8  823.73   865.2  834.58
   914.1  839.91   923.9  841.88   933.7  845.47   982.6  866.52  1031.6  885.34
  1051.1   890.6  1129.4  900.97  1178.4  905.62  1325.2  929.58  1344.8  933.93
#Mann= 3 , 0 , 0
       0      .1       0   561.5    .045       0   581.9     .05       0
Bank Sta=561.5,581.9
XS Rating Curve= 0 ,0
Exp/Cntr=0.3,0.1

Type RM Length L Ch R = 1 ,46388.7 ,373.2,372.8,371.8
XS GIS Cut Line= 4
     1583505.425      219223.642     1583709.418      219635.968
     1583752.821      219774.857     1583843.967      220525.725
#Sta/Elev= 30
       0  971.54    58.7  944.61   117.4  918.97   166.4  900.57   264.3  865.36
   293.6  854.97   313.2  848.94   342.6  841.12   381.7  831.76   391.5  829.73
   401.3  828.41   518.2  822.26   537.6   821.1   548.6  822.12   566.7  825.45
   576.4   826.4     635  828.78   792.2  831.77   831.5   831.9   910.1  831.16
   988.6  833.42  1008.3  834.47  1027.9  837.42  1155.6  861.77  1214.6  870.31
  1224.4  873.01  1253.9  885.42  1312.8  907.49  1332.4  912.41  1361.9  917.71
#Mann= 3 , 0 , 0
       0     .05       0   518.2     .04       0   548.6     .05       0
#XS Ineff= 2 , 0
                           580.6          836.08
Permanent Ineff=
       F       F
Bank Sta=518.2,548.6
XS Rating Curve= 0 ,0
Exp/Cntr=0.3,0.1

Type RM Length L Ch R = 1 ,46015.9 ,292.6,301.3,309.9
XS GIS Cut Line= 4
      1583273.22      219299.597     1583327.474      219590.395
     1583403.429      219809.579     1583524.957      220415.048
#Sta/Elev= 30
       0  965.78    76.3  934.08   162.2  899.74   200.4  885.33   267.2  862.06
   276.7   858.8   286.3  856.13   344.1   845.9   373.1  840.02   382.8  837.18
   392.5  833.46   411.8  824.06   421.5  820.58   431.1  819.74   440.8  820.83
   450.5  823.22   460.1  824.57   518.1  825.57   576.8  827.62   674.8  832.69
   733.6  836.23   782.6  840.18   880.7  849.65   919.9  853.83   949.3  857.27
   968.9  860.16  1008.1  867.78  1047.3   874.7  1066.9  878.93  1145.3  899.22
#Mann= 3 , 0 , 0
       0     .08       0   411.8     .04       0   450.5     .05       0
Bank Sta=411.8,450.5
XS Rating Curve= 0 ,0
Exp/Cntr=0.3,0.1

Type RM Length L Ch R = 1 ,45714.6 ,48.4,48.7,49
XS GIS Cut Line= 4
     1583124.349      219361.663     1583093.099      219776.593
     1583087.891      219890.308     1583113.932      220324.336
#Sta/Elev= 30
       0  959.12    48.4  940.07   154.8  898.93   183.9  888.19   193.5  884.29
   222.6  871.56   232.2  868.48   251.6  864.12   261.3  861.46   319.3  843.64
   338.7  838.21     358  834.51   425.6  824.57   444.6  821.37     454  819.98
   463.5   819.6     473  819.82   482.5  821.37     492  824.06   501.5  825.81
   520.4   827.1   568.6   827.5   607.2  829.15   790.8   842.7   819.8  844.04
   858.5  844.86   868.1  845.38   897.1  847.64   935.8  852.22   964.8  855.02
#Mann= 3 , 0 , 0
       0     .05       0   444.6     .04       0     492     .05       0
Bank Sta=444.6,492
XS Rating Curve= 0 ,0
Exp/Cntr=0.3,0.1

Type RM Length L Ch R = 1 ,45665.9 ,151.7,148.7,145.6
XS GIS Cut Line= 4
     1583071.398      219362.531     1583047.526      219757.496
     1583038.845      219900.725     1583058.377      220304.371
#Sta/Elev= 30
       0  965.49   135.1  911.39   173.7  896.86     193  888.19   202.7  884.46
     222  878.75   279.9  859.19   289.5   856.4   318.5  849.31   357.1  839.08
   376.4  834.58   395.7     831     434  826.74   443.5  825.28   453.1  822.84
   462.6  820.39   472.2  819.64   481.8  820.09   491.4  821.86   500.9  824.37
   510.5  825.34   529.6  826.13   616.2  828.07   635.4  828.96   673.9  831.75
   741.2  838.55   779.7  841.86     799  842.85   866.3  844.86   943.3   850.7
#Mann= 3 , 0 , 0
       0     .05       0   453.1     .04       0   500.9     .05       0
Bank Sta=453.1,500.9
XS Rating Curve= 0 ,0
Exp/Cntr=0.3,0.1

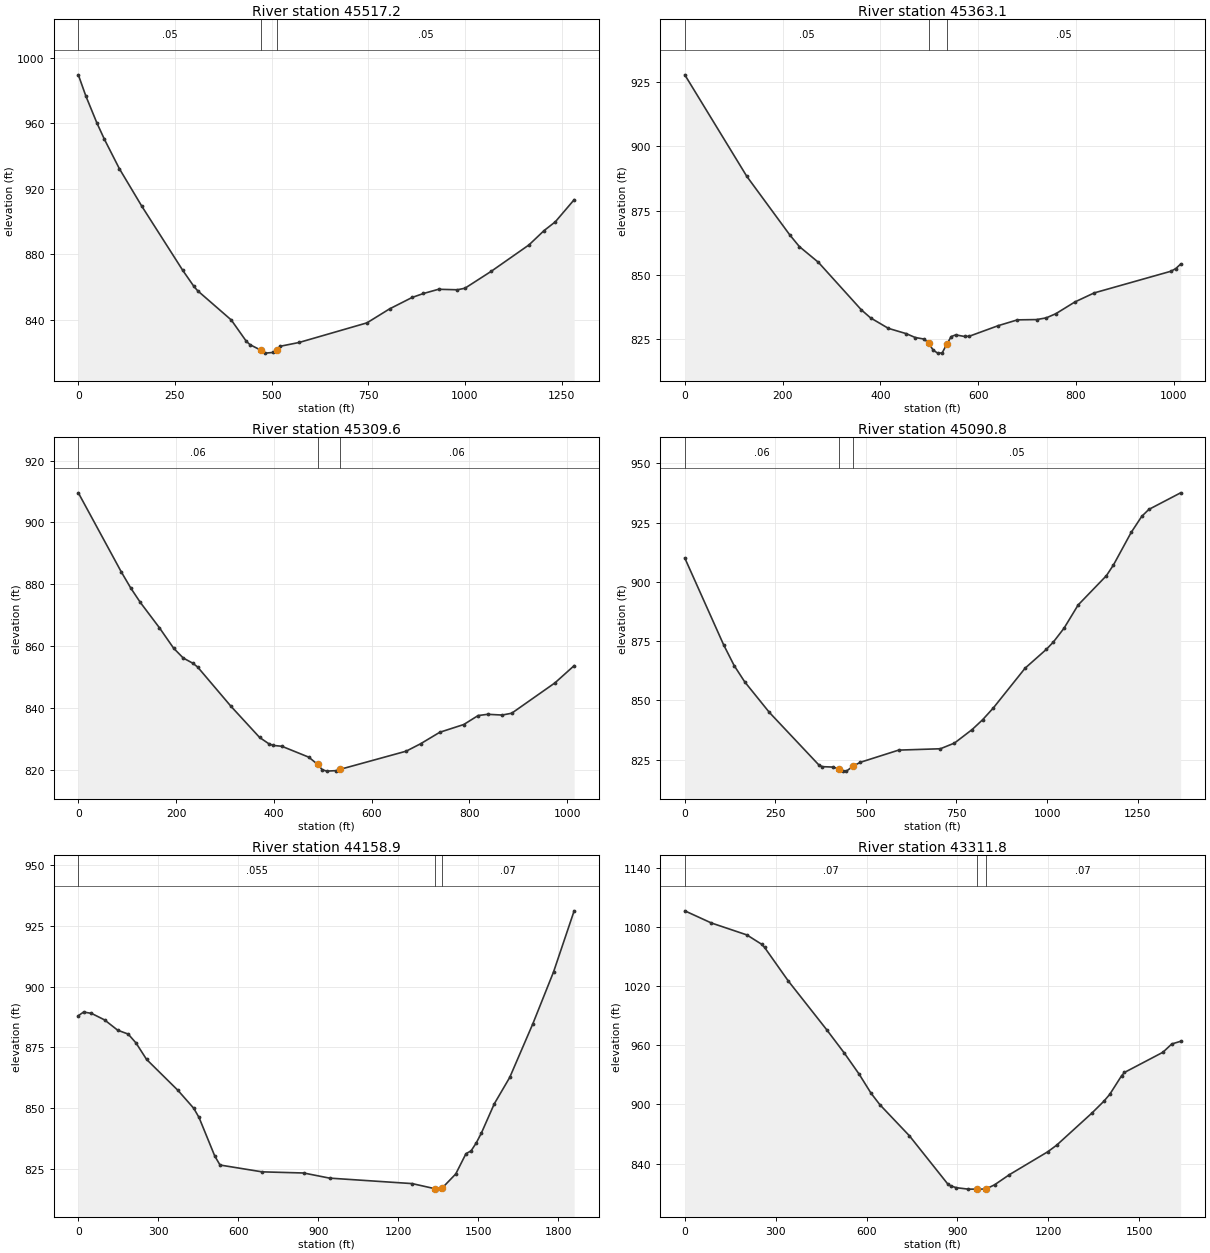
Type RM Length L Ch R = 1 ,45517.2 ,158.8,154.1,149.4
XS GIS Cut Line= 4
     1582868.707      219370.777      1582889.54      219756.194
     1582903.429      219950.638     1582927.734      220652.027
#Sta/Elev= 30
       0  989.57    19.3  976.72    48.2  960.06    67.6  950.14   106.1  932.28
     164  909.41   270.2  870.13   299.1  860.32   308.8  857.67   395.7  839.83
   434.7  826.79   444.5  824.72   473.7  821.21   483.4   819.6   502.9  819.99
   512.7   821.6   522.4   823.8   571.2  826.11   746.6  838.08   805.1  846.61
   863.6  853.61   892.8  856.02   931.8  858.59   980.6   858.3  1000.1  859.23
  1068.3  869.59  1165.8  885.69  1204.8  894.43    1234  899.81  1282.7   913.3
#Mann= 3 , 0 , 0
       0     .05       0   473.7     .04       0   512.7     .05       0
Bank Sta=473.7,512.7
XS Rating Curve= 0 ,0
Exp/Cntr=0.3,0.1

Type RM Length L Ch R = 1 ,45363.1 ,53.5,53.5,53.5
XS GIS Cut Line= 5
     1582542.318      219429.805     1582681.207      219773.555
      1582735.46       219858.19     1582763.238      219955.413
     1582806.207      220395.083
#Sta/Elev= 30
       0  927.62   126.8  888.26   214.6  865.58   234.2  861.04   273.2  854.93
     361  836.51   379.9  833.38   416.4  829.31     453  827.25   471.3  825.76
   489.7  825.14   498.9  823.51     508  820.89   517.2   819.7   526.4  819.77
   535.6  823.07   544.8   826.1     554  826.78   572.4  826.15   582.2  826.27
   641.1  830.35   680.4   832.6   719.6  832.71   739.3  833.37   758.9  834.98
   798.2  839.57   837.4  843.05   994.5  851.46  1004.3  852.49  1014.2  854.22
#Mann= 3 , 0 , 0
       0     .05       0   498.9     .04       0   535.6     .05       0
Bank Sta=498.9,535.6
XS Rating Curve= 0 ,0
Exp/Cntr=0.3,0.1

Type RM Length L Ch R = 1 ,45309.6 ,211.5,218.8,225.8
XS GIS Cut Line= 5
      1582491.97      219447.166     1582630.859      219790.916
     1582685.113      219875.551     1582712.891      219972.774
     1582755.859      220412.444
#Sta/Elev= 30
       0  909.57    87.8  884.02   107.3  878.77   126.8  874.14   165.9  865.94
   195.1   859.3   214.6  856.17   234.2  854.48   243.9  853.28   312.2  840.56
   370.8  830.49     389  828.52   398.2  827.92   416.4  827.63   471.3  824.12
   489.7  821.75   498.9  820.07     508   819.6   526.4  819.75   535.6  820.18
   670.6  826.05     700  828.44   739.3  832.16   788.4  834.67   817.8  837.57
   837.4  837.97   866.9  837.73   886.5  838.32   974.9  848.13  1014.2   853.7
#Mann= 3 , 0 , 0
       0     .06       0   489.7     .04       0   535.6     .06       0
Bank Sta=489.7,535.6
XS Rating Curve= 0 ,0
Exp/Cntr=0.3,0.1

Type RM Length L Ch R = 1 ,45090.8 ,919.7,931.9,943.6
XS GIS Cut Line= 5
     1582445.095      219415.916     1582490.234      219763.138
      1582483.29      219926.333     1582472.873      220127.722
     1582281.901      220752.722
#Sta/Elev= 30
       0  910.07     107  873.51   136.2   864.7   165.4  857.81   233.4  844.92
   369.4  822.84     379  822.02   407.8  821.85     427  821.05   436.6  820.23
   446.2  820.13   465.4  822.32   484.7  823.86   590.3     829   705.5  829.57
   744.4  831.97   793.2  837.68   822.4  841.86   851.7   846.8   939.5   863.6
     998  871.52  1017.5  874.64  1046.8  880.44  1085.8  890.26  1163.8  902.62
  1183.3  907.15  1232.1  920.85  1261.4  927.66  1280.9  930.58  1368.7  937.59
#Mann= 3 , 0 , 0
       0     .06       0     427    .045       0   465.4     .05       0
Bank Sta=427,465.4
XS Rating Curve= 0 ,0
Exp/Cntr=0.3,0.1

Type RM Length L Ch R = 1 ,44158.9 ,860.3,847.1,832.1
XS GIS Cut Line= 5
     1582531.901      218815.222      1581952.04      219332.583
     1581618.707      219697.166     1581511.068      219867.305
      1581452.04      220249.249
#Sta/Elev= 30
       0  888.03    19.7  889.54    49.2     889    98.4   886.3   147.6  882.05
   186.9  880.46   216.4  876.77   255.8  870.02   373.8  857.21   432.8  849.84
   452.5  846.06   511.5  830.17   531.2  826.46   688.6  823.65   844.9  823.17
   941.8  821.06  1251.7   818.8  1338.2  816.66  1357.4  816.52  1364.1  816.98
  1414.9  822.77  1453.3  831.14  1472.4  832.29  1491.8  835.56  1511.1  839.65
  1559.4  851.69  1617.4   862.6  1704.3  884.79  1781.6  906.08  1858.9  931.28
#Mann= 3 , 0 , 0
       0    .055       0  1338.2    .045       0  1364.1     .07       0
Bank Sta=1338.2,1364.1
XS Rating Curve= 0 ,0
Exp/Cntr=0.3,0.1

Type RM Length L Ch R = 1 ,43311.8 ,1785.9,1790.4,1790.7
XS GIS Cut Line= 4
      1580954.21      218896.385     1580836.154      219618.607
      1580856.12        219947.6     1580968.967      220511.836
#Sta/Elev= 30
       0 1096.35    87.8 1084.01   204.9 1071.91   253.7 1062.43   263.4 1059.21
   341.5 1025.24   468.4  975.72   526.9  951.92   575.7  930.57   614.7  911.35
     644  899.64   741.5   868.1   867.5  819.44   877.2  817.37   896.6  815.44
   935.4     814   964.5     814   993.6  814.06  1022.6  818.39  1071.2  828.59
  1197.9  851.85  1227.2   858.5  1344.2  891.24  1383.2  903.12  1402.8  910.14
  1441.8  928.99  1451.5   932.4  1578.3  952.85  1607.6  961.28  1636.8  963.97
#Mann= 3 , 0 , 0
       0     .07       0   964.5    .045       0   993.6     .07       0
Bank Sta=964.5,993.6
XS Rating Curve= 0 ,0
Exp/Cntr=0.3,0.1

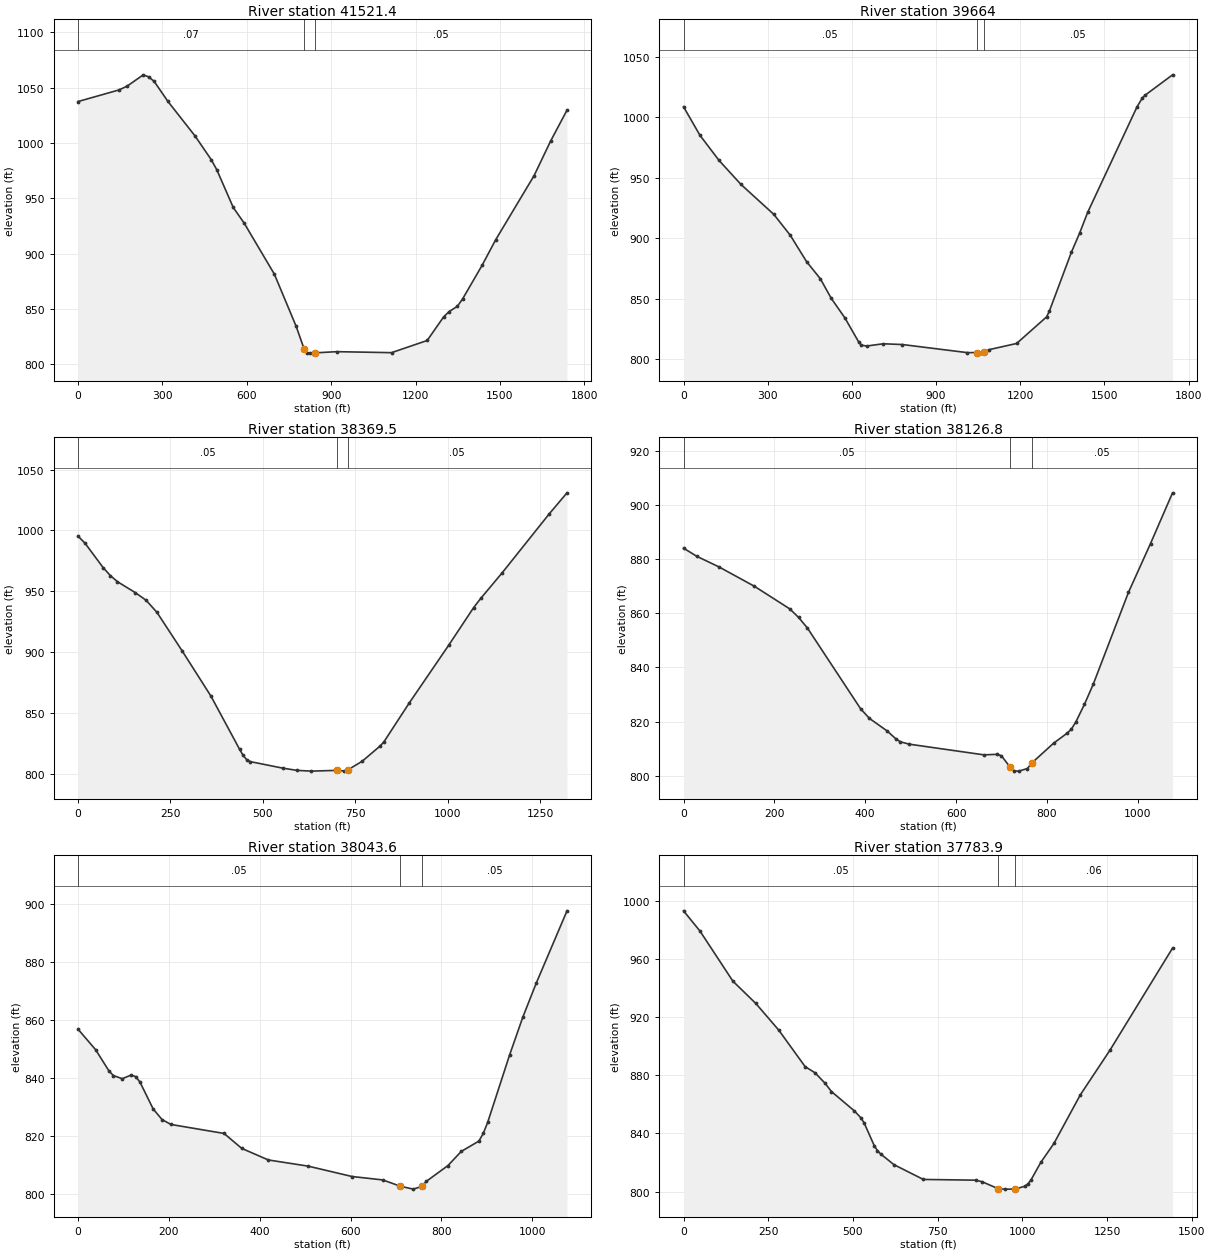
Type RM Length L Ch R = 1 ,41521.4 ,1870.3,1857.4,1842
XS GIS Cut Line= 5
      1578954.21      219201.072      1579204.21       219603.85
      1579266.71      219819.128     1579273.654      220030.933
     1579332.682      220857.322
#Sta/Elev= 30
       0 1037.46   145.1 1047.92   174.1 1051.31   232.2 1061.62   251.5 1059.73
   270.9 1055.66   319.3 1037.74     416 1006.42   474.1   984.8   493.6  975.78
     552  941.74     591  927.51   698.2  881.46   775.3  834.55   804.2  813.72
   813.8  810.28   823.4   810.1   842.7  810.34   919.9  811.42  1114.8  810.52
  1241.5  821.52    1300  842.83  1319.5  847.67  1348.8  852.39  1368.2  859.42
  1436.5  889.36  1485.2  912.62  1621.7  970.56  1680.2 1001.68  1738.6  1029.7
#Mann= 3 , 0 , 0
       0     .07       0   804.2    .045       0   842.7     .05       0
Bank Sta=804.2,842.7
XS Rating Curve= 0 ,0
Exp/Cntr=0.3,0.1

Type RM Length L Ch R = 1 ,39664   ,1287.2,1294.5,1285.9
XS GIS Cut Line= 5
     1577361.762      220084.753     1577919.054       220657.67
     1578028.429      220803.503     1578158.637      220949.336
     1578450.304      221433.711
#Sta/Elev= 30
       0 1008.61    58.5  985.02   126.7  964.19   204.7  944.39   321.6  919.66
   380.1  902.44   438.6   880.5   487.4  866.43   526.3  850.23   575.1  833.98
   623.8  814.24   633.6  811.46     653  810.79   711.5  812.63   779.8  812.01
  1010.9  805.32 1045.18805.3271  1059.8   804.9  1069.5  805.76  1089.1  807.79
  1186.8  812.88    1294  834.94  1303.8  839.78  1381.8  888.19    1411  903.92
  1440.3  921.43  1615.7 1008.44  1635.2 1016.05    1645 1018.24  1742.5 1035.03
#Mann= 3 , 0 , 0
       0     .05       0 1045.18    .045       0  1069.5     .05       0
Bank Sta=1045.18,1069.5
XS Rating Curve= 0 ,0
Exp/Cntr=0.3,0.1

Type RM Length L Ch R = 1 ,38369.5 ,252.3,242.7,232.6
XS GIS Cut Line= 4
     1576918.186      220598.208     1577222.005      221162.444
      1577295.79      221344.736     1577512.804      221778.763
#Sta/Elev= 30
       0   995.4    19.4  989.43      68  969.52    87.4  963.04   106.8  957.97
   155.4  948.93   184.5  942.65   213.6   932.8   281.6  901.26   359.3  864.24
   436.9  820.55   446.6  815.47   456.4   811.9   466.1   810.3   553.4  804.98
   592.3  803.11   631.1   802.5   699.8  803.12   719.5  802.67   729.3  803.41
   768.7  810.59   817.8  823.25   827.7   826.6   895.7  858.26  1002.5   905.7
  1070.4  936.77  1089.8  944.37  1148.1   965.5  1274.2 1013.43  1322.8  1030.9
#Mann= 3 , 0 , 0
       0     .05       0   699.8     .04       0   729.3     .05       0
Bank Sta=699.8,729.3
XS Rating Curve= 0 ,0
Exp/Cntr=0.3,0.1

Type RM Length L Ch R = 1 ,38126.8 ,83.5,83.1,84.3
XS GIS Cut Line= 5
     1576637.804      220702.157     1576900.825      221157.887
     1576997.179      221290.699     1577070.095       221366.22
     1577213.325      221608.407
#Sta/Elev= 30
       0  884.03    29.2  881.01      78   877.1   155.9  869.96   233.9   861.6
   253.4  858.43   272.8  854.52   389.8  824.73   409.2  821.17   448.2  816.54
   467.7  813.59   477.5  812.52     497  811.65   661.3  807.71   690.3   807.9
   699.8  807.39   718.9  803.19   728.4  801.74     738   801.7   757.1  802.66
   766.6  804.69   814.6  811.99   843.8  815.62   853.5  817.14   863.2  819.69
   882.6  826.35     902  833.77   979.6  867.72  1028.1  885.72  1076.6  904.45
#Mann= 3 , 0 , 0
       0     .05       0   718.9     .04       0   766.6     .05       0
Bank Sta=718.9,766.6
XS Rating Curve= 0 ,0
Exp/Cntr=0.3,0.1

Type RM Length L Ch R = 1 ,38043.6 ,257.6,259.7,261.4
XS GIS Cut Line= 5
     1576562.283      220730.803     1576825.304      221186.532
     1576921.658      221319.345     1576994.575      221394.866
     1577137.804      221637.053
#Sta/Elev= 30
       0  856.87      39  849.74    68.2  842.45      78  840.85    97.4  839.78
   116.9  841.03   126.7  840.52   136.4  838.64   165.6  829.31   185.1  825.69
   204.6     824   321.6   820.9   360.5  815.75     419  811.76   506.7  809.63
   603.4  806.05     671  804.87   709.4  802.72     738   801.7   757.1  802.64
   766.6  804.35   814.6  809.84   843.8   814.7   882.6  818.26   892.3  820.92
     902  824.74   950.5  848.09   979.6  861.12  1008.7  872.66  1076.6  897.67
#Mann= 3 , 0 , 0
       0     .05       0   709.4     .04       0   757.1     .05       0
Bank Sta=709.4,757.1
XS Rating Curve= 0 ,0
Exp/Cntr=0.3,0.1

Type RM Length L Ch R = 1 ,37783.9 ,668.2,663,656.7
XS GIS Cut Line= 5
      1576041.45      220869.692     1576528.429      221255.109
     1576695.095      221442.609     1576820.095        221562.4
     1577067.491        221874.9
#Sta/Elev= 30
       0     993    48.5   979.1   145.6  944.69   213.5   929.3   281.4  910.91
     359  885.89   388.2  881.67   417.3   874.6   436.7  868.79   504.6  855.41
     524  850.63   533.7  846.94   562.8  831.68   572.5   828.1   582.2  825.82
     621  818.54   707.9  808.36   862.3  807.86   881.5  806.77   929.6  801.93
   947.7   801.7   977.7  801.71  1006.6  803.58  1016.2  805.17  1025.8  808.04
  1054.8  820.13  1093.6  833.17  1171.4  866.54  1258.9  897.23  1443.6   967.4
#Mann= 3 , 0 , 0
       0     .05       0   929.6    .045       0   977.7     .06       0
Bank Sta=929.6,977.7
XS Rating Curve= 0 ,0
Exp/Cntr=0.3,0.1

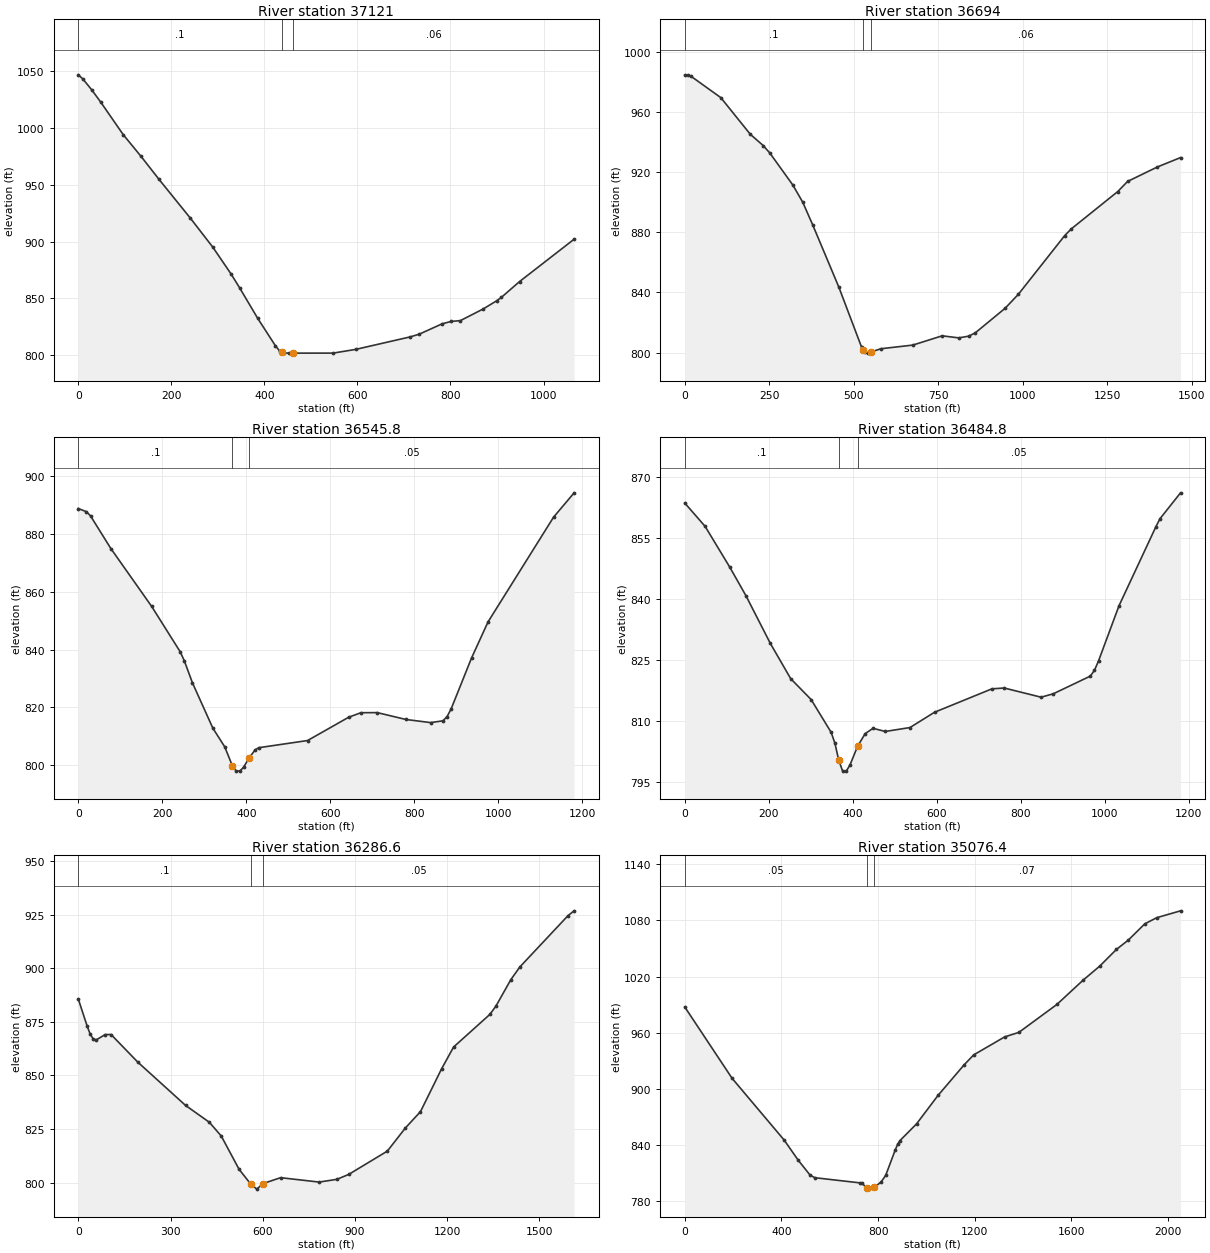
Type RM Length L Ch R = 1 ,37121   ,432.3,426.9,421.2
XS GIS Cut Line= 4
     1575812.283      221431.324     1576119.575      221592.782
     1576301.866      221715.178     1576684.679      222035.491
#Sta/Elev= 30
       0 1047.02     9.6 1043.44    28.9 1033.72    48.2 1022.94    96.4  994.35
     135  975.04   173.6  954.79   241.1  920.55   289.3  894.98   327.8  871.81
   347.1  859.02   385.3  832.58   423.5  808.31     433  803.45   436.8  802.86
   442.6  801.95   452.1   801.7   461.7   801.7   547.6  801.72   596.1  804.97
   713.5  816.02   733.1  818.44     782  827.52   801.6  829.66   821.2  830.34
   870.1  840.57   899.5  847.89   909.2  850.76   948.4  864.75  1065.8  902.12
#Mann= 3 , 0 , 0
       0      .1       0   436.8    .045       0   461.7     .06       0
Bank Sta=436.8,461.7
XS Rating Curve= 0 ,0
Exp/Cntr=0.3,0.1

Type RM Length L Ch R = 1 ,36694   ,149,148.2,147.4
XS GIS Cut Line= 4
     1575614.366      221821.949     1576064.887      222048.512
       1576260.2      222121.428     1576971.137      222374.032
#Sta/Elev= 30
       0  984.36     9.7  984.67    19.4  983.57   106.7  969.52     194  945.15
   232.8  937.53   252.1   932.6     320  911.38   349.1  900.02   378.2  885.17
   455.8  843.67   523.2  803.71   528.4  801.78   532.7  800.18   542.2  799.68
   551.7  800.47   580.1  802.59   674.9  805.02   761.8  811.18   810.8  809.82
   840.1  810.95   859.7  813.14   947.9  829.46   987.1  838.74  1124.3  877.78
  1143.9  882.27  1281.1  907.02  1310.5   913.8  1398.6  923.42  1467.2  929.66
#Mann= 3 , 0 , 0
       0      .1       0   528.4    .045       0   551.7     .06       0
Bank Sta=528.4,551.7
XS Rating Curve= 0 ,0
Exp/Cntr=0.3,0.1

Type RM Length L Ch R = 1 ,36545.8 ,61.1,61.1,61.1
XS GIS Cut Line= 4
     1575682.075      222048.512     1575994.575      222181.324
     1576088.325      222212.574     1576812.283      222374.032
#Sta/Elev= 30
       0  888.77    19.4  887.67    29.1   886.2    77.6   874.9   174.6  854.92
   242.5  839.24   252.2  836.16   271.6  828.52   320.2  812.83   348.5  806.38
   366.5  799.88   375.5  798.04   384.5  797.98   393.4  799.34  406.39802.4897
   420.4  805.27   429.4  806.08   545.7  808.56   643.3   816.6   672.6  818.18
   711.6  818.21     780  815.83   838.5  814.76   867.8  815.37   877.6  816.81
   887.3  819.47   936.1  837.15   975.2  849.57  1131.3  885.81  1180.1   894.2
#Mann= 3 , 0 , 0
       0      .1       0   366.5    .045       0  406.39     .05       0
Bank Sta=366.5,406.39
XS Rating Curve= 0 ,0
Exp/Cntr=0.3,0.1

Type RM Length L Ch R = 1 ,36484.8 ,199.3,198.2,197
XS GIS Cut Line= 4
     1575656.033      222104.067     1575968.533       222236.88
     1576062.283       222268.13     1576786.241      222429.588
#Sta/Elev= 30
       0  863.54    48.5  857.79   106.7  847.85   145.5  840.78   203.7  829.03
   252.2  820.36   300.8  815.23   348.5  807.16   357.5  804.47   366.5  800.31
   375.5  797.73   384.5  797.63   393.4  799.17   411.4  803.73   429.4  806.84
   448.1  808.15   477.4  807.38     536  808.34   594.5   812.1   731.2  817.86
   760.4  818.06   848.3   815.8   877.6  816.66   965.4  820.99   975.2  822.41
   984.9  824.72  1033.7   838.3  1121.6  857.74  1131.3  859.69  1180.1  866.04
#Mann= 3 , 0 , 0
       0      .1       0   366.5    .045       0   411.4     .05       0
Bank Sta=366.5,411.4
XS Rating Curve= 0 ,0
Exp/Cntr=0.3,0.1

Type RM Length L Ch R = 1 ,36286.6 ,1198.6,1210.2,1219.2
XS GIS Cut Line= 5
     1575324.566      222345.213     1575816.753       222386.88
     1575946.962      222423.338     1576282.899      222509.275
      1576795.92       222886.88
#Sta/Elev= 30
       0  885.54    29.1  872.81    38.7  869.19    48.4  866.99    58.1  866.52
    87.2  869.02   106.5  869.05   193.7  856.14   348.7  836.01   426.2  828.14
   464.9  821.74   522.9  806.22   561.6  799.18   580.9  796.96   600.2  799.52
   658.1   802.3   783.3  800.25   841.1  801.52   879.6  803.82  1005.3  814.69
  1064.1  825.49  1113.1  833.09  1181.7  853.04  1220.9  863.23  1338.5  878.39
  1358.1  882.18  1407.1  894.65  1436.5  900.57  1593.3  924.52  1612.9  926.72
#Mann= 3 , 0 , 0
       0      .1       0   561.6    .045       0   600.2     .05       0
Bank Sta=561.6,600.2
XS Rating Curve= 0 ,0
Exp/Cntr=0.3,0.1

Type RM Length L Ch R = 1 ,35076.4 ,1657,1660.3,1662.1
XS GIS Cut Line= 4
     1575303.733      222892.088     1575774.211       223403.98
     1575875.774      223495.126     1576857.545      224219.084
#Sta/Elev= 30
       0  987.55   195.8  911.38   411.3  845.42     470  823.72     519  807.88
   538.6  805.19   724.5  799.71   734.2  799.08   753.7  794.18   763.4  793.01
     783  794.85   812.2  800.48   831.7  807.81   871.1  834.87   880.9  840.84
   890.8   844.9   959.6  862.82  1048.1   893.1  1156.4  925.83  1195.7  936.37
  1323.6  955.54  1382.6  960.41    1540  990.24  1648.2 1016.12  1717.1 1031.12
    1786 1048.94  1835.1 1058.86    1904 1076.37  1953.2 1082.89  2051.6 1090.21
#Mann= 3 , 0 , 0
       0     .05       0   753.7    .045       0     783     .07       0
Bank Sta=753.7,783
XS Rating Curve= 0 ,0
Exp/Cntr=0.3,0.1