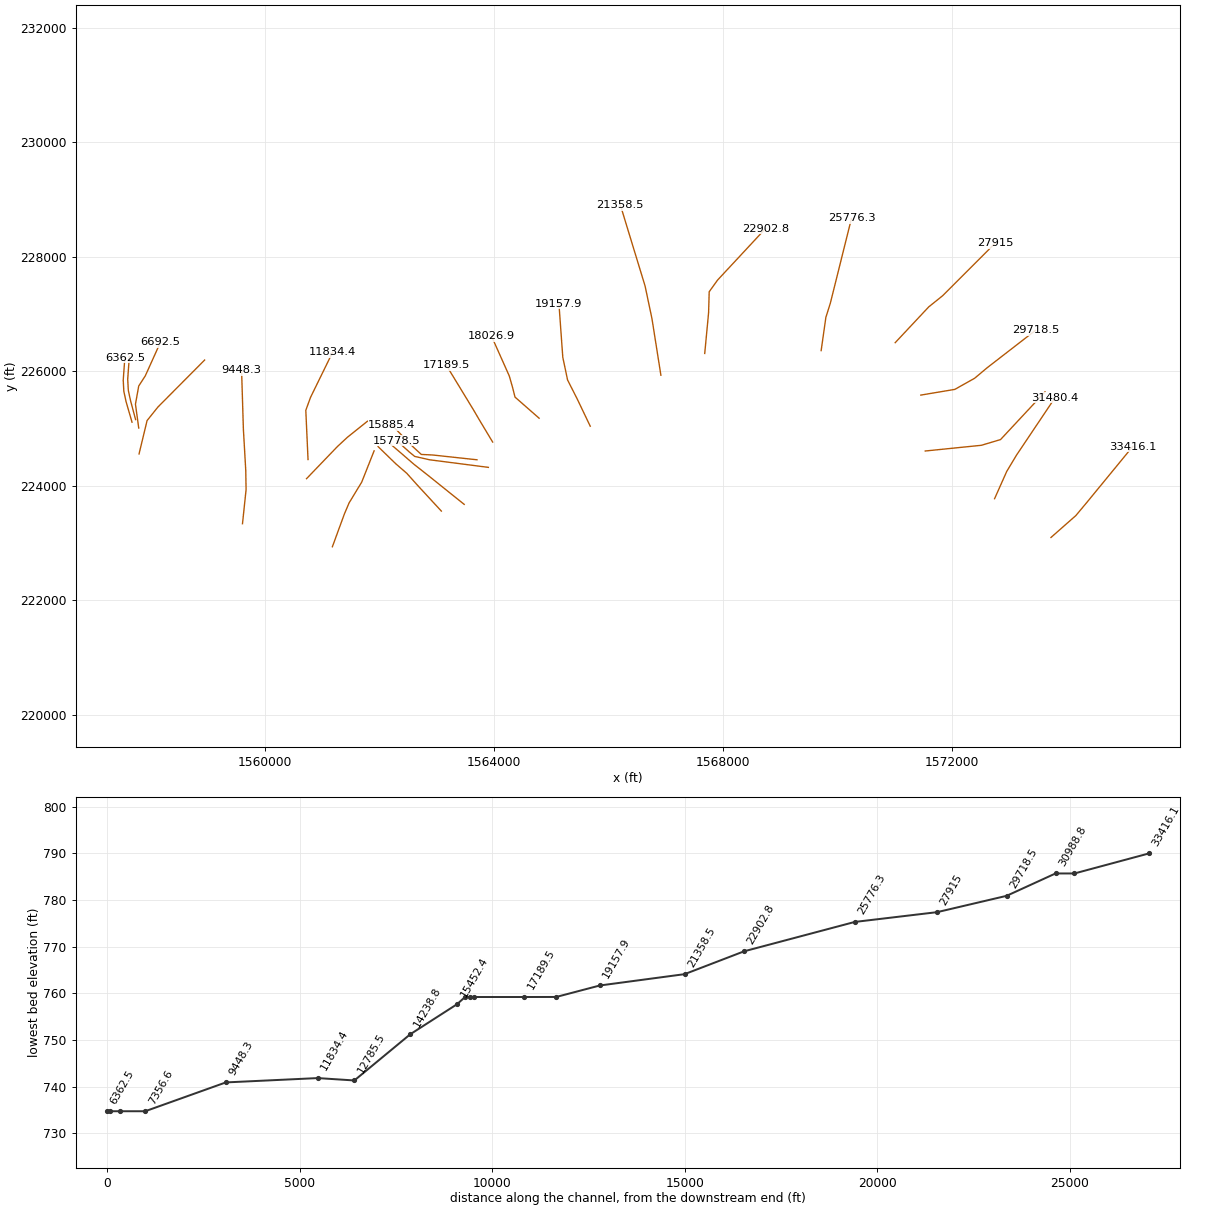
HEC-RAS study BNCR.prj: BNCR

--- BNCR.g01 (geometry) --- (continued)

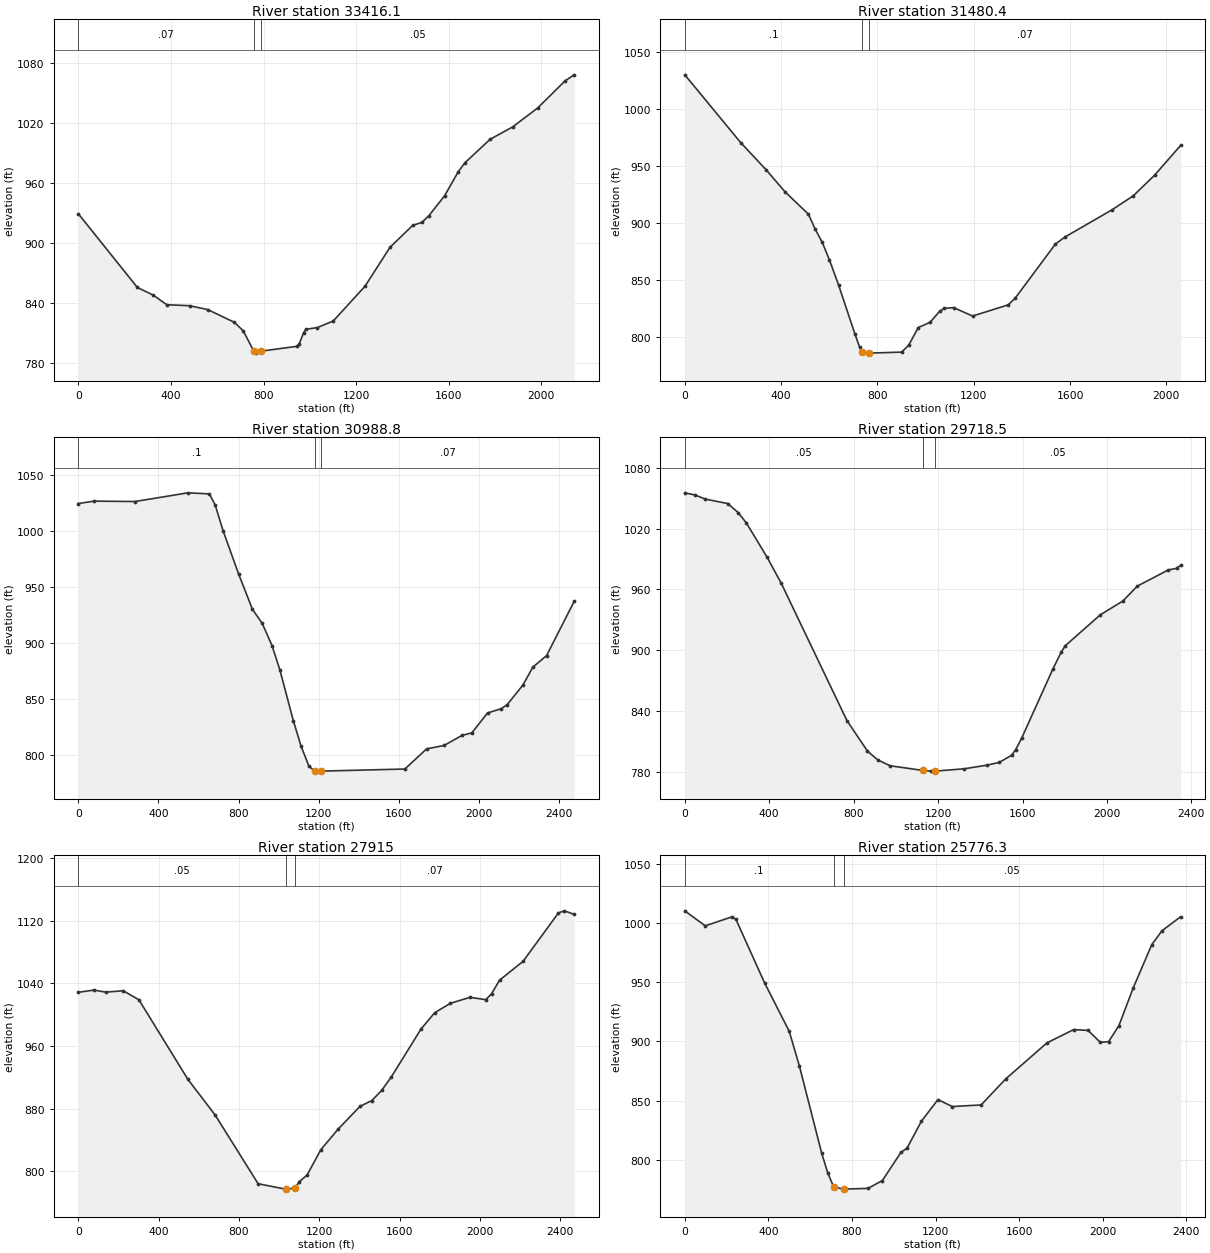
Type RM Length L Ch R = 1 ,33416.1 ,1931.1,1935.7,1939.1
XS GIS Cut Line= 4
     1573726.476      223097.817     1574160.503      223479.762
     1574338.455      223692.435     1575154.427      224686.359
#Sta/Elev= 30
       0  929.07   254.8  855.55   323.4   847.9   382.2  838.28   480.2  837.33
   558.6  833.46   673.8  820.77     712  812.33   757.7  792.03   769.4     790
   788.5  791.95   943.8  796.78   953.6   798.9   973.2  810.52   983.1  813.78
  1032.2  815.52  1100.9  822.03  1238.3   856.8  1346.3  895.68  1444.4  917.52
  1483.7  920.47  1513.2   926.9  1581.9  947.01  1640.8  971.02  1670.2  980.06
  1778.2 1003.33  1876.4 1015.79  1984.4 1034.75  2102.2 1061.67  2141.4  1067.7
#Mann= 3 , 0 , 0
       0     .07       0   757.7    .045       0   788.5     .05       0
Bank Sta=757.7,788.5
XS Rating Curve= 0 ,0
Exp/Cntr=0.3,0.1

Type RM Length L Ch R = 1 ,31480.4 ,508.6,491.5,474.2
XS GIS Cut Line= 4
     1572741.233        223774.9     1572953.906      224252.331
     1573123.177      224534.449      1573795.92      225537.053
#Sta/Elev= 30
       0 1029.74   232.3  970.26   338.8  946.23   416.2  927.14     513  907.65
     542  894.18     571  882.76   600.1  867.73   638.8  845.31   706.5  802.44
   725.9  790.88   735.5  786.75   754.9   785.7   764.6   785.7   900.7   786.6
   930.2  792.79   969.4  808.13  1018.5  812.69  1057.8  822.27  1077.4  824.99
  1116.7  825.58  1195.2  818.22  1342.5     828  1371.9  833.86  1538.8   881.3
  1578.1  887.46  1774.4  911.41  1862.7  923.72  1951.1  941.75    2059  967.85
#Mann= 3 , 0 , 0
       0      .1       0   735.5    .045       0   764.6     .07       0
Bank Sta=735.5,764.6
XS Rating Curve= 0 ,0
Exp/Cntr=0.3,0.1

Type RM Length L Ch R = 1 ,30988.8 ,1260.2,1270.3,1280.6
XS GIS Cut Line= 4
     1571530.295      224608.234     1572511.198       224708.06
     1572845.399      224807.887     1573622.309       225641.22
#Sta/Elev= 30
       0 1024.34    78.1 1026.47   283.1 1026.14   546.7 1033.88   654.1 1032.92
   683.4 1022.78   722.4    1000   800.5  961.15   868.8     930   917.6  917.46
   966.4  897.71  1005.4  876.14  1073.2  830.44  1111.9  807.69  1150.7  790.08
  1179.7  785.71  1188.1   785.7  1208.8   785.7  1629.4  787.57  1737.4  805.47
  1825.8  808.68  1914.2  817.54  1963.4  819.81  2041.9  837.59  2110.7  841.38
  2140.1  845.06  2218.7   862.5  2267.8   878.4  2336.6  888.74  2474.1  937.07
#Mann= 3 , 0 , 0
       0      .1       0  1179.7    .045       0  1208.8     .07       0
Bank Sta=1179.7,1208.8
XS Rating Curve= 0 ,0
Exp/Cntr=0.3,0.1

Type RM Length L Ch R = 1 ,29718.5 ,1806.3,1803.4,1792
XS GIS Cut Line= 5
      1571452.17      225584.796     1572046.788      225684.623
      1572394.01      225879.935     1572611.024      226062.227
     1573453.038      226713.268
#Sta/Elev= 30
       0 1055.24    48.6 1053.14    97.2 1049.05   204.2 1044.63   252.8 1035.76
   291.7 1025.56     389  992.08   457.1  966.03   768.1  830.76   865.3  800.69
   913.9  792.01   972.2   786.2  1128.4  781.58  1167.5   780.9    1187  780.93
  1323.8   783.2  1431.2  786.76  1489.8  789.51  1548.4  796.56  1567.9  802.17
  1597.2  813.95  1743.7  881.49  1782.7  897.93  1802.3  904.48  1968.3  934.93
  2075.7  948.61    2144   963.3  2290.5  979.21  2329.6   980.8  2349.1  983.79
#Mann= 3 , 0 , 0
       0     .05       0  1128.4    .045       0    1187     .05       0
Bank Sta=1128.4,1187
XS Rating Curve= 0 ,0
Exp/Cntr=0.3,0.1

Type RM Length L Ch R = 1 ,27915   ,2124.7,2138.8,2151.4
XS GIS Cut Line= 4
     1571005.121      226500.595     1571591.059      227125.595
     1571834.115      227320.907     1572754.253      228241.046
#Sta/Elev= 30
       0 1028.64    77.9 1031.48   136.3 1028.85   223.9 1030.62   301.8 1019.06
   545.2  917.74   681.5  871.98   895.7  784.27  1032.1  777.41  1041.8   777.4
  1080.8  779.04  1100.3  786.88  1139.3  795.29  1207.6  827.59  1295.7  854.46
  1403.3  883.11    1462  890.46    1511  903.43  1559.9  920.93  1706.6  981.62
  1775.1 1002.59  1853.4 1014.56  1951.2 1022.24  2029.5 1019.23  2058.9 1026.97
    2098 1044.11  2215.4 1068.16  2391.5 1129.98  2420.9 1132.63  2469.8 1128.18
#Mann= 3 , 0 , 0
       0     .05       0  1032.1    .045       0  1080.8     .07       0
Bank Sta=1032.1,1080.8
XS Rating Curve= 0 ,0
Exp/Cntr=0.3,0.1

Type RM Length L Ch R = 1 ,25776.3 ,2912.3,2873.5,2897.8
XS GIS Cut Line= 4
     1569711.719      226361.706     1569794.184      226943.303
     1569872.309      227190.699     1570241.233      228670.734
#Sta/Elev= 30
       0 1010.16    97.9  997.48   225.2 1005.05   244.8  1002.9   381.8   949.3
   499.3  908.64   548.2  879.25   654.7  805.81   683.5  789.19   712.3  777.15
   760.4   775.3   876.4  775.94   945.3  782.54  1033.8  806.25  1063.4   809.9
  1132.2  832.65    1211  850.86  1279.8     845  1417.6  846.34  1535.7  868.36
  1732.5   898.7  1860.4  909.93  1929.3  909.27  1988.4  899.13  2027.8  899.78
    2077  913.28  2145.8  945.29  2234.4  981.68  2283.6  993.46  2372.2 1005.16
#Mann= 3 , 0 , 0
       0      .1       0   712.3    .045       0   760.4     .05       0
Bank Sta=712.3,760.4
XS Rating Curve= 0 ,0
Exp/Cntr=0.3,0.1

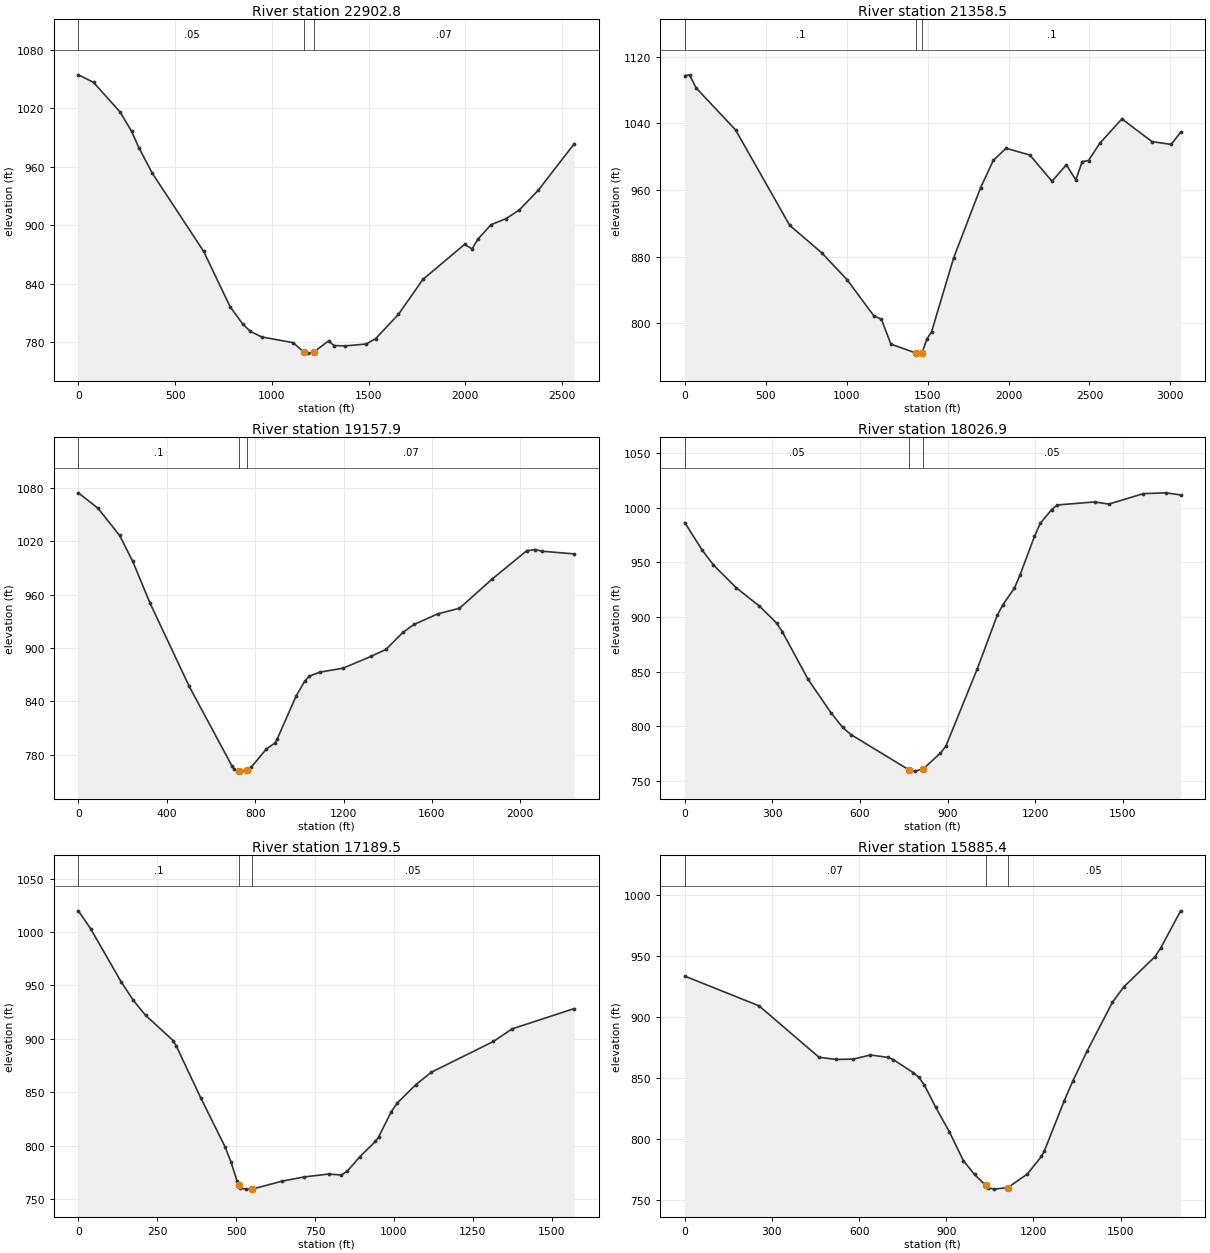
Type RM Length L Ch R = 1 ,22902.8 ,1523.6,1544.3,1563.5
XS GIS Cut Line= 5
     1567677.865      226312.227     1567745.573      227025.768
      1567755.99      227390.352     1567901.823      227593.477
     1568740.365      228494.518
#Sta/Elev= 30
       0 1054.45    78.6 1046.74     216 1016.27   274.9   996.6   314.2   979.2
   382.9  953.28     648  873.27   783.9  816.74   851.1   798.5   889.5  791.22
   947.1  785.64  1110.3  779.72    1168  769.67  1187.3     769  1216.1  770.04
  1293.1  781.54  1321.9  776.73  1380.4  776.47  1487.8  778.34  1536.7   783.9
  1653.9  808.69  1780.9  844.63  1995.8  880.51  2034.9  875.92  2064.2  885.74
  2132.6  900.72  2210.7     907  2279.1  915.87  2376.8  936.06  2562.4  983.63
#Mann= 3 , 0 , 0
       0     .05       0    1168    .045       0  1216.1     .07       0
Bank Sta=1168,1216.1
XS Rating Curve= 0 ,0
Exp/Cntr=0.3,0.1

Type RM Length L Ch R = 1 ,21358.5 ,2193.9,2200.6,2205.4
XS GIS Cut Line= 5
      1566912.24      225932.018      1566755.99      226921.602
     1566677.865      227291.393     1566636.198       227489.31
     1566203.906      228905.977
#Sta/Elev= 30
       0 1097.16    29.5 1098.14    68.8  1082.7   314.3 1031.84   648.2  917.44
   844.7  884.76  1001.8  852.46  1166.6  809.22    1215  804.56  1273.2   774.9
    1428  764.24  1447.2   764.1  1466.5  764.71  1495.4  780.93  1524.3  789.62
  1660.5  878.21  1827.3  962.68  1905.8  995.39  1984.2 1009.98  2131.4  1001.9
  2268.7  970.41    2357  990.15  2415.8  972.05    2455  993.96  2494.3   995.3
    2563  1015.8  2700.3 1045.23  2886.6 1017.97  3004.4 1014.65  3063.2 1029.15
#Mann= 3 , 0 , 0
       0      .1       0    1428    .045       0  1466.5      .1       0
Bank Sta=1428,1466.5
XS Rating Curve= 0 ,0
Exp/Cntr=0.3,0.1

Type RM Length L Ch R = 1 ,19157.9 ,1135.1,1131,1127.4
XS GIS Cut Line= 5
     1565677.865      225041.393     1565448.698       225520.56
     1565282.031      225848.685     1565198.698      226244.518
      1565130.99      227182.018
#Sta/Elev= 30
       0 1074.48    88.5 1057.26   186.9 1026.57   245.9  997.61   324.6  950.42
   501.6  857.03   695.8  767.21   705.5   763.7   724.8  761.67   763.6  762.53
     783  766.32   850.8  786.49   889.5  793.25   899.2  797.42   985.9  846.34
  1024.4  862.69  1043.6  868.24  1091.8  872.91  1197.7  877.37  1323.3  890.55
  1391.8  898.48  1470.1   917.9  1519.1  926.55  1626.8  938.48  1724.7  944.75
  1871.6  977.37  2028.2 1009.26  2067.4 1010.76  2096.8 1008.89  2243.6 1005.86
#Mann= 3 , 0 , 0
       0      .1       0   724.8    .045       0   763.6     .07       0
Bank Sta=724.8,763.6
XS Rating Curve= 0 ,0
Exp/Cntr=0.3,0.1

Type RM Length L Ch R = 1 ,18026.9 ,831.8,837.4,842.9
XS GIS Cut Line= 5
     1564784.635       225181.15     1564363.628      225550.074
     1564324.566      225706.324     1564263.802      225918.998
     1563955.642      226609.102
#Sta/Elev= 30
       0   986.2    58.9  961.34    98.2  947.49   176.8  926.55   255.3  910.03
   314.3  894.52   333.9  886.51   422.3  842.97   500.8  812.48   540.1  799.25
   569.2  792.55   768.9  760.16   788.2  759.21     817  761.37   874.7  775.47
   893.9  781.99  1000.9  852.26  1069.6  901.42  1089.2  911.31  1128.5  926.32
  1148.1  938.57  1197.2  973.56  1216.8  985.43  1256.1  998.15  1275.7 1002.35
  1403.3  1005.1  1452.4 1003.17  1570.2 1012.71  1648.7 1013.43  1697.8 1011.49
#Mann= 3 , 0 , 0
       0     .05       0   768.9    .045       0     817     .05       0
Bank Sta=768.9,817
XS Rating Curve= 0 ,0
Exp/Cntr=0.3,0.1

Type RM Length L Ch R = 1 ,17189.5 ,1297.4,1304.2,1310.8
XS GIS Cut Line= 4
     1563973.003      224764.484     1563738.628      225155.109
     1563647.483      225311.359     1563161.371       226109.97
#Sta/Elev= 30
       0 1019.86    38.8 1003.22   135.7  953.39   174.5  935.95   213.2  922.01
   300.5  898.34   310.2  893.42   387.7  844.89   465.1   798.8   484.1  784.44
   503.2   766.5  508.28763.1171   512.7  760.17   531.7   759.2   550.8  759.22
   646.3  766.71   715.2   770.6   793.9  773.36   833.3  772.39   852.9  776.19
   892.3   789.6   941.5  803.87   951.4  807.86   990.7  831.14  1010.4  839.73
  1069.4  857.03  1118.7  868.68  1315.5  897.51  1374.5  909.28  1571.4   928.3
#Mann= 3 , 0 , 0
       0      .1       0  508.28    .045       0   550.8     .05       0
Bank Sta=508.28,550.8
XS Rating Curve= 0 ,0
Exp/Cntr=0.3,0.1

Type RM Length L Ch R = 1 ,15885.4 ,105.8,106.9,108.3
XS GIS Cut Line= 5
      1563699.92      224454.762     1562927.865      224538.355
     1562726.685      224548.338     1562578.906      224684.189
     1562211.205      225062.834
#Sta/Elev= 30
       0  933.72   255.6  909.35     462  867.21     521  865.45     580  865.71
     639  869.09   697.9  867.18   717.6  865.34   786.2  854.66   805.3  850.89
   824.5  844.55   862.9  826.57   910.8  806.09   958.8  782.54   997.1  771.23
  1035.4  762.38  1044.9  760.24    1064   759.2  1111.8  760.43  1178.7  771.57
  1227.6  786.04  1237.4  790.41  1305.8  831.54  1335.1  847.57    1384  872.03
    1472  912.37    1511  924.94  1618.6  949.72  1638.1  956.78  1706.5   987.2
#Mann= 3 , 0 , 0
       0     .07       0  1035.4     .04       0  1111.8     .05       0
Bank Sta=1035.4,1111.8
XS Rating Curve= 0 ,0
Exp/Cntr=0.3,0.1

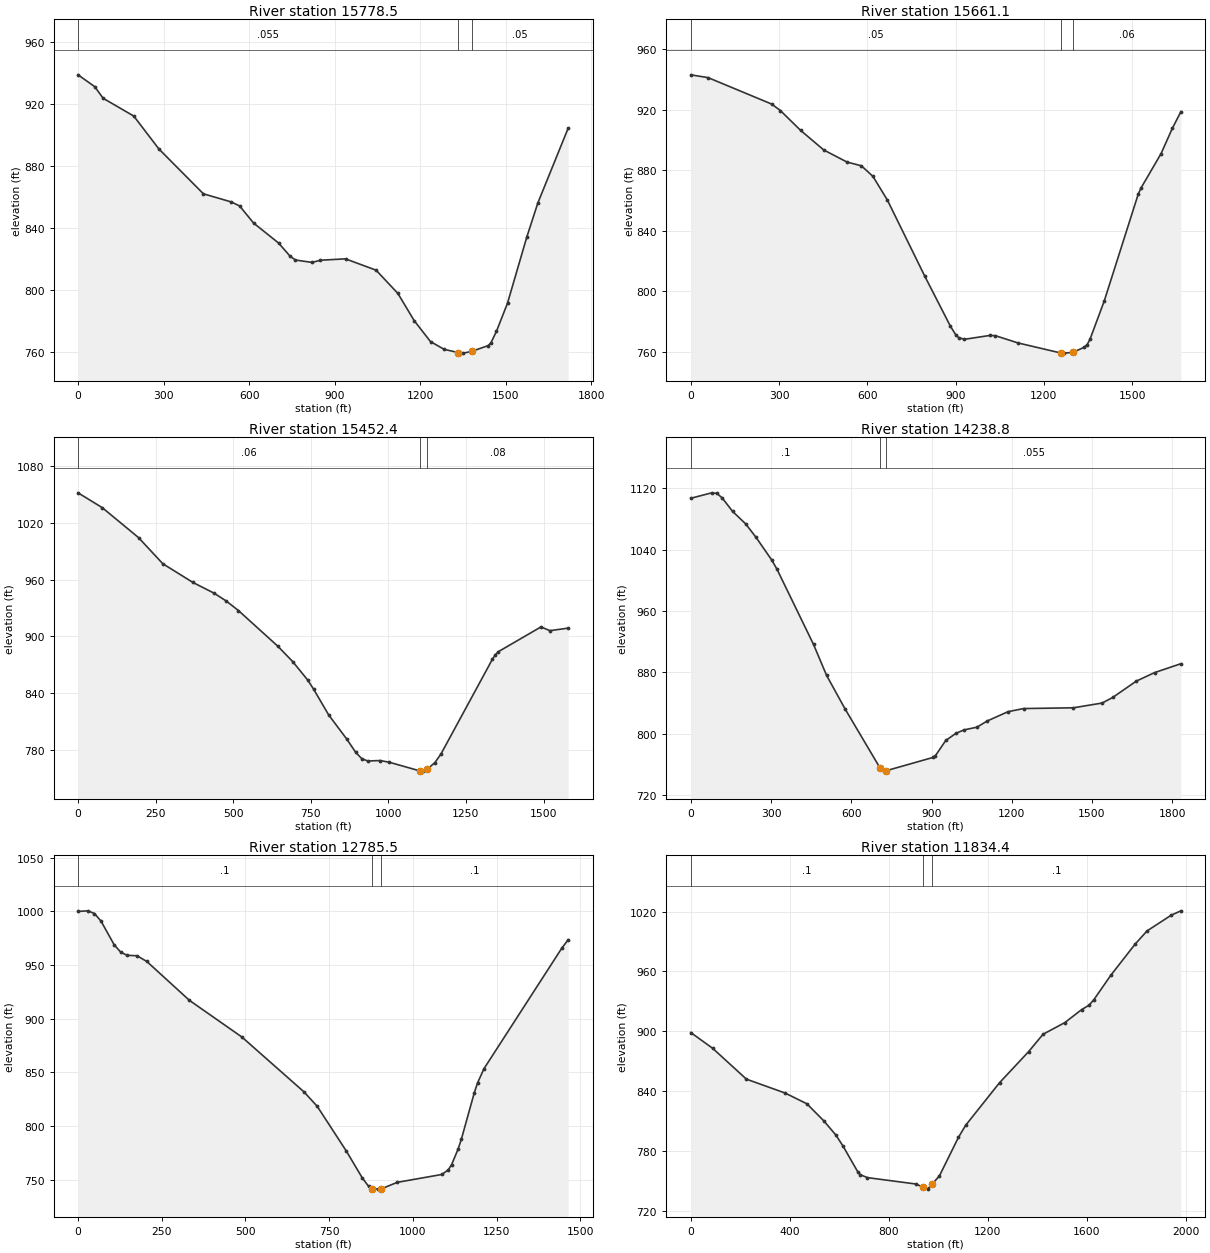
Type RM Length L Ch R = 1 ,15778.5 ,115.7,117.4,117.1
XS GIS Cut Line= 5
     1563898.705      224322.383     1562871.795      224454.762
     1562611.379      224513.789     1562514.156       224593.65
     1562299.313      224788.529
#Sta/Elev= 30
       0  938.64    58.6  930.99    87.9  923.53   195.4  912.05   283.3  890.86
   439.6  861.91   537.2  856.69   566.5  854.09   615.4  843.07   703.3  830.16
   742.4   821.9   761.9  819.24   820.5  817.69   849.8   819.1   937.7  819.99
  1044.9  812.68  1121.2  797.71  1178.4  780.17  1235.7  766.63  1283.4  761.66
  1331.5   759.6  1350.8   759.2  1379.9  760.31  1437.9  764.05  1447.6  765.87
  1466.9  773.25  1505.6   791.4  1573.3  834.05    1612  856.03  1718.3  904.24
#Mann= 3 , 0 , 0
       0    .055       0  1331.5     .04       0  1379.9     .05       0
Bank Sta=1331.5,1379.9
XS Rating Curve= 0 ,0
Exp/Cntr=0.3,0.1

Type RM Length L Ch R = 1 ,15661.1 ,210.6,208.6,208
XS GIS Cut Line= 5
     1563476.042      223675.942     1562863.115      224167.869
     1562592.281      224381.411     1562399.653      224548.338
     1562187.334      224730.369
#Sta/Elev= 30
       0   942.9    58.9  941.04   275.1  923.58   304.5   919.3   373.3  906.22
   451.9   893.3   530.5  885.35   579.6  882.86   618.9  875.89     668  860.25
   795.5  809.84   881.7  777.16   900.9  771.13   910.5  769.44   929.6  768.31
  1015.8  770.88    1035  770.73  1111.6  765.95  1258.3  759.25  1268.1  759.21
  1297.5  759.67  1336.7  763.04  1346.5  764.77  1356.3  768.23    1405  793.68
  1520.7  864.33  1530.4   868.4  1597.9  890.88  1636.4  907.64  1665.4  918.61
#Mann= 3 , 0 , 0
       0     .05       0  1258.3    .045       0  1297.5     .06       0
Bank Sta=1258.3,1297.5
XS Rating Curve= 0 ,0
Exp/Cntr=0.3,0.1

Type RM Length L Ch R = 1 ,15452.4 ,1241.6,1213.7,1185
XS GIS Cut Line= 5
     1563077.091      223558.494     1562660.424      224009.883
     1562472.924       224218.65     1562280.295      224385.578
     1561972.135      224685.057
#Sta/Elev= 30
       0 1051.82      78 1036.16     195 1004.48     273  976.92   370.5  957.04
   438.8  945.69   477.8  937.42   516.8  927.42   643.3  889.85   691.7  873.46
   740.1  853.95   759.4  844.13   807.8  817.01   865.9  791.58   894.9  777.45
   914.5   770.8   934.1  768.36   973.3  768.85  1002.7  767.07  1100.8  757.97
  1110.6  757.66 1125.54759.8314  1149.8  766.59  1169.3  775.62  1335.4  875.95
  1345.1  880.73  1354.9     884  1491.6  910.05  1520.9  906.13  1579.5  908.82
#Mann= 3 , 0 , 0
       0     .06       0  1100.8    .045       0 1125.54     .08       0
Bank Sta=1100.8,1125.54
XS Rating Curve= 0 ,0
Exp/Cntr=0.3,0.1

Type RM Length L Ch R = 1 ,14238.8 ,1462.8,1453.3,1443.7
XS GIS Cut Line= 5
     1561173.524      222935.925     1561381.858      223504.501
     1561464.323      223699.814     1561685.677      224064.397
     1561902.691      224611.272
#Sta/Elev= 30
       0 1107.15    78.1 1114.28    97.7 1113.44   117.2 1107.72   156.3 1090.05
   205.1 1073.82   244.2 1056.08   302.8 1026.52   322.3 1014.61     459  916.43
   507.9  875.99   576.2  832.74  707.93755.1117   721.2  751.22   730.8  751.78
   904.8     769   914.5  771.29   953.3  791.26     992  800.63  1021.1  804.97
  1069.6  808.52  1108.4  816.65  1185.9  828.75  1244.1  832.85  1430.4  833.84
  1538.2  840.07  1577.5  847.35  1665.7  868.67  1734.4  879.81  1832.4  891.36
#Mann= 3 , 0 , 0
       0      .1       0  707.93    .045       0   730.8    .055       0
Bank Sta=707.93,730.8
XS Rating Curve= 0 ,0
Exp/Cntr=0.3,0.1

Type RM Length L Ch R = 1 ,12785.5 ,940.7,951.1,961.2
XS GIS Cut Line= 4
     1560722.135      224125.161      1561264.67      224689.397
     1561438.281      224849.987     1561785.503      225127.765
#Sta/Elev= 30
       0  999.96    29.4 1000.51    48.9  998.02    68.5     991   107.6  969.08
   127.2  962.07   146.8  959.05   176.1  958.69   205.5  953.32   332.7  917.11
   489.2  883.01   675.1  831.81   714.3  818.47   801.7  776.58     849  751.71
   867.9  743.91   877.4  741.78   896.3   741.3   905.7  741.51     953  747.59
  1086.9  754.98  1106.2   759.4  1115.9  764.22  1135.2  778.63  1144.9  787.78
  1183.6  831.17  1193.2  840.21  1212.6  853.56  1444.6  965.62  1463.9  973.59
#Mann= 3 , 0 , 0
       0      .1       0   877.4    .045       0   905.7      .1       0
Bank Sta=877.4,905.7
XS Rating Curve= 0 ,0
Exp/Cntr=0.3,0.1

Type RM Length L Ch R = 1 ,11834.4 ,2379.2,2386.1,2392.9
XS GIS Cut Line= 4
     1560748.177      224459.362     1560709.115      225318.737
      1560791.58      225544.432     1561177.865      226334.362
#Sta/Elev= 30
       0  898.71      88  883.01   224.8  852.01   381.2  838.09   469.2  827.29
   537.7  810.14   586.5  795.86   615.9  784.55   674.5  759.18   684.3  756.33
   713.6  753.34   908.3  746.98   937.2     744   956.4  741.81   975.6  747.01
  1004.4   755.1  1081.3  793.73  1110.3  805.76  1247.1  848.41  1364.4  879.51
    1423     897  1510.9  908.68  1579.3  921.78  1608.6  926.06  1628.1  931.58
  1696.5  956.04  1794.2  987.11  1843.1 1000.56  1940.8 1016.33  1979.9 1020.69
#Mann= 3 , 0 , 0
       0      .1       0   937.2    .045       0   975.6      .1       0
Bank Sta=937.2,975.6
XS Rating Curve= 0 ,0
Exp/Cntr=0.3,0.1

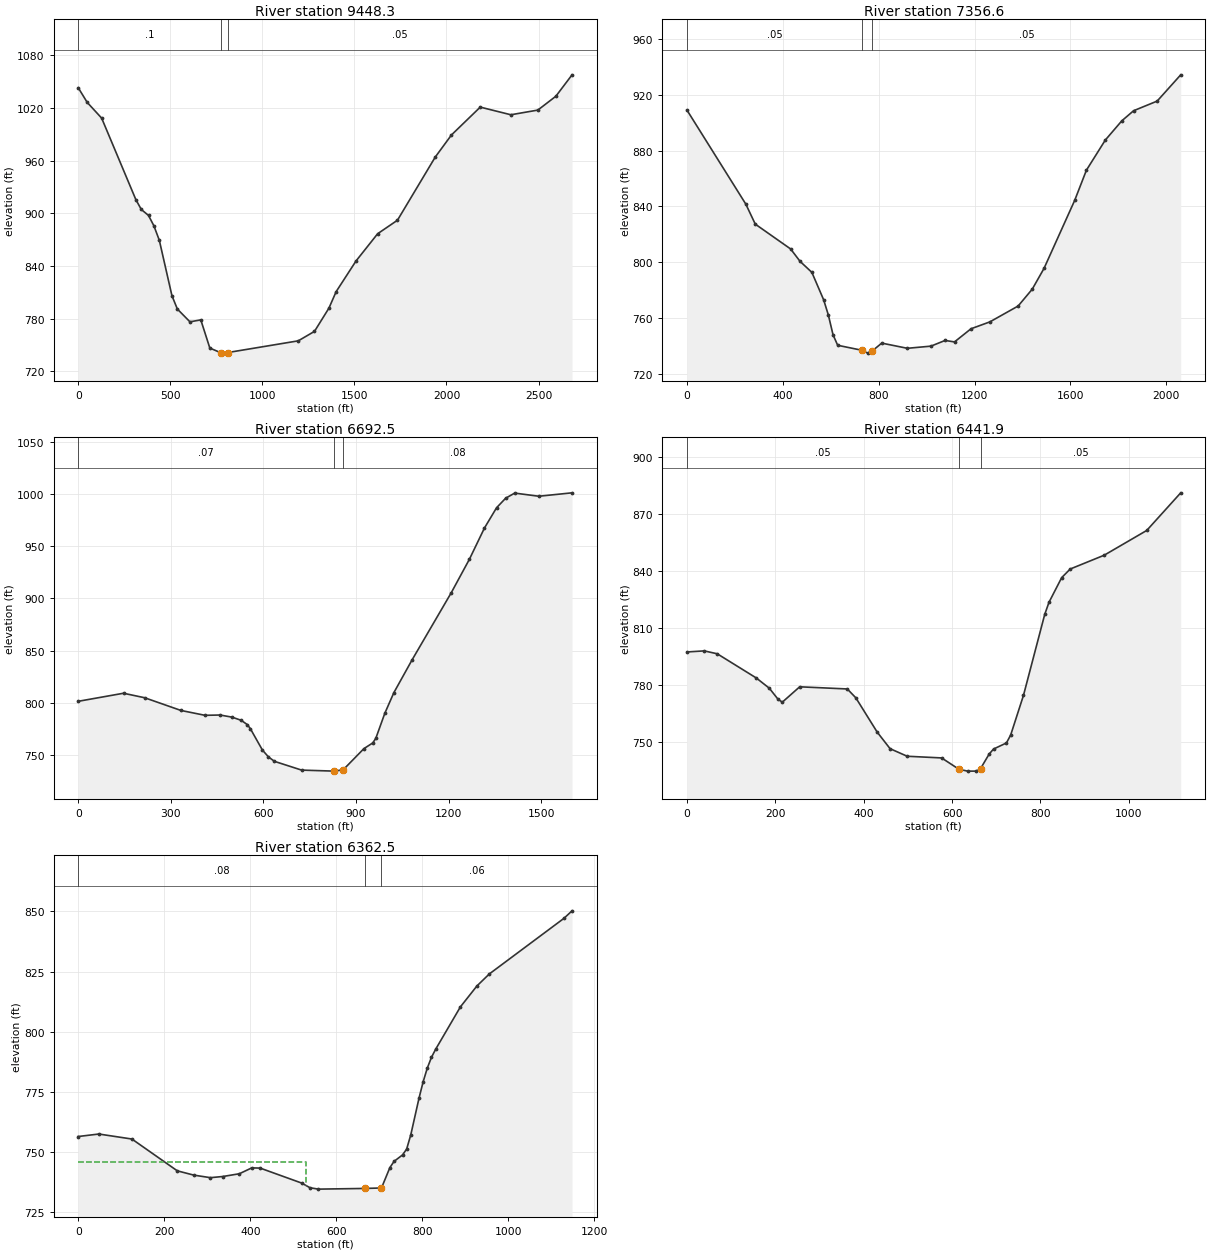
Type RM Length L Ch R = 1 ,9448.3  ,2106.9,2091.7,2075.6
XS GIS Cut Line= 5
     1559603.212      223337.834     1559665.712      223931.584
     1559660.503      224264.918     1559618.837      224988.876
     1559587.587      226014.918
#Sta/Elev= 30
       0  1042.9    48.9 1026.17   127.2 1008.32   313.2  915.46   342.6  904.37
   381.7  897.56   411.1  885.68   440.4  869.31   508.9  806.28   538.3  791.06
   606.8  776.49   665.7  778.73   714.7  746.66   773.5  741.38   793.1  740.88
   811.2  741.51    1195  754.86  1283.2  765.65  1361.6  792.09  1400.8  810.84
  1508.6  845.71  1626.2  876.76  1733.8  892.13  1939.1  964.01  2027.1  989.16
  2183.5 1020.85  2349.7 1012.15  2496.3 1017.48  2594.1 1033.22  2682.1  1057.6
#Mann= 3 , 0 , 0
       0      .1       0   773.5    .045       0   811.2     .05       0
Bank Sta=773.5,811.2
XS Rating Curve= 0 ,0
Exp/Cntr=0.3,0.1

Type RM Length L Ch R = 1 ,7356.6  ,661.4,664.1,666
XS GIS Cut Line= 4
      1557795.92      224556.584     1557936.545      225139.918
     1558124.045      225374.293     1558941.753      226197.209
#Sta/Elev= 30
       0  909.07   245.9  841.55   285.3  827.22   432.8  809.41   472.2  800.51
   521.4  792.62   570.5  772.95   590.2  762.02   609.7  747.86   629.1  740.32
  730.69736.7372     755   734.7   774.3  736.43     813  741.88   919.8  738.16
  1018.2  739.71  1077.2  743.79  1116.5  742.74  1185.3  752.17    1264  757.11
  1381.9  768.48  1440.9  780.59  1490.1  795.52  1617.9  844.26    1667  865.97
  1745.7  887.53  1814.5  901.31  1863.7  908.56    1962  915.47  2060.3  934.31
#Mann= 3 , 0 , 0
       0     .05       0  730.69    .045       0   774.3     .05       0
Bank Sta=730.69,774.3
XS Rating Curve= 0 ,0
Exp/Cntr=0.3,0.1

Type RM Length L Ch R = 1 ,6692.5  ,236.2,250.6,264.9
XS GIS Cut Line= 5
     1557790.712      225009.709      1557733.42      225426.376
     1557790.712      225744.084     1557905.295      225921.168
      1558170.92      226509.709
#Sta/Elev= 30
       0  801.52   146.7  809.23   215.2  804.93   332.6  792.78   410.8  788.11
   459.7   788.4   498.8  786.32   528.2   783.3   547.8  779.21   557.6  775.38
   596.7  754.89   616.2  748.33   635.8  744.05   723.8  735.68   829.7   734.7
   858.5  735.98   925.6  756.23   954.3   761.7   964.1  766.03   993.5  790.18
  1022.8  809.88  1081.5  841.08  1208.7  905.47  1267.4  937.46  1316.3  967.43
  1355.5  986.79  1384.8  995.86  1414.2 1000.77  1492.4  997.76    1600 1001.03
#Mann= 3 , 0 , 0
       0     .07       0   829.7    .045       0   858.5     .08       0
Bank Sta=829.7,858.5
XS Rating Curve= 0 ,0
Exp/Cntr=0.3,0.1

Type RM Length L Ch R = 1 ,6441.9  ,79.3,79.4,79.3
XS GIS Cut Line= 5
     1557735.655      225156.845     1557647.483      225488.876
      1557608.42      225668.564     1557598.003      225863.876
     1557626.649      226257.105
#Sta/Elev= 30
       0  797.34    39.3  797.91    68.7  796.38     157  783.67   186.5  778.28
   206.1  772.52   215.9  770.95   255.2  779.03   362.9  777.89   382.2  773.24
   430.6  755.19   459.7   746.5   498.4  742.52   576.3  741.64   615.4   735.7
     635   734.7   654.6   734.7   664.3     736   683.9  743.68   693.7   746.3
     723  749.52   732.6  753.71   761.5   774.5   809.6  817.09   819.2  823.44
     848  836.44   867.3  840.95   944.2  848.21  1040.4  861.22  1117.3     881
#Mann= 3 , 0 , 0
       0     .05       0   615.4     .04       0   664.3     .05       0
Bank Sta=615.4,664.3
XS Rating Curve= 0 ,0
Exp/Cntr=0.3,0.1

Type RM Length L Ch R = 1 ,6362.5  ,129.8,122.9,115.8
XS GIS Cut Line= 5
     1557673.155      225111.706     1557569.358      225471.515
     1557530.295      225651.203     1557519.878      225846.515
     1557548.524      226239.744
#Sta/Elev= 30
       0  756.55      48  757.58   124.8   755.5   230.4  742.29   268.9  740.51
   307.3  739.46   336.1  739.94   374.5  741.08   403.5  743.52   422.9  743.44
   519.6  737.21     539  735.26   558.4   734.7   665.9  734.98   705.1  735.18
   724.6  743.63   734.4  746.24     754   748.9   763.6  751.32   773.2  757.23
   792.4   772.5     802   779.3   811.6  784.95   821.3  789.43   830.9  792.74
   888.6  810.38     927  819.06   955.9  824.06    1129  847.09  1148.2  850.26
#Mann= 3 , 0 , 0
       0     .08       0   665.9     .04       0   705.1     .06       0
#XS Ineff= 2 , 0
          529.77  746.08
Permanent Ineff=
       F       F
Bank Sta=665.9,705.1
XS Rating Curve= 0 ,0
Exp/Cntr=0.3,0.1