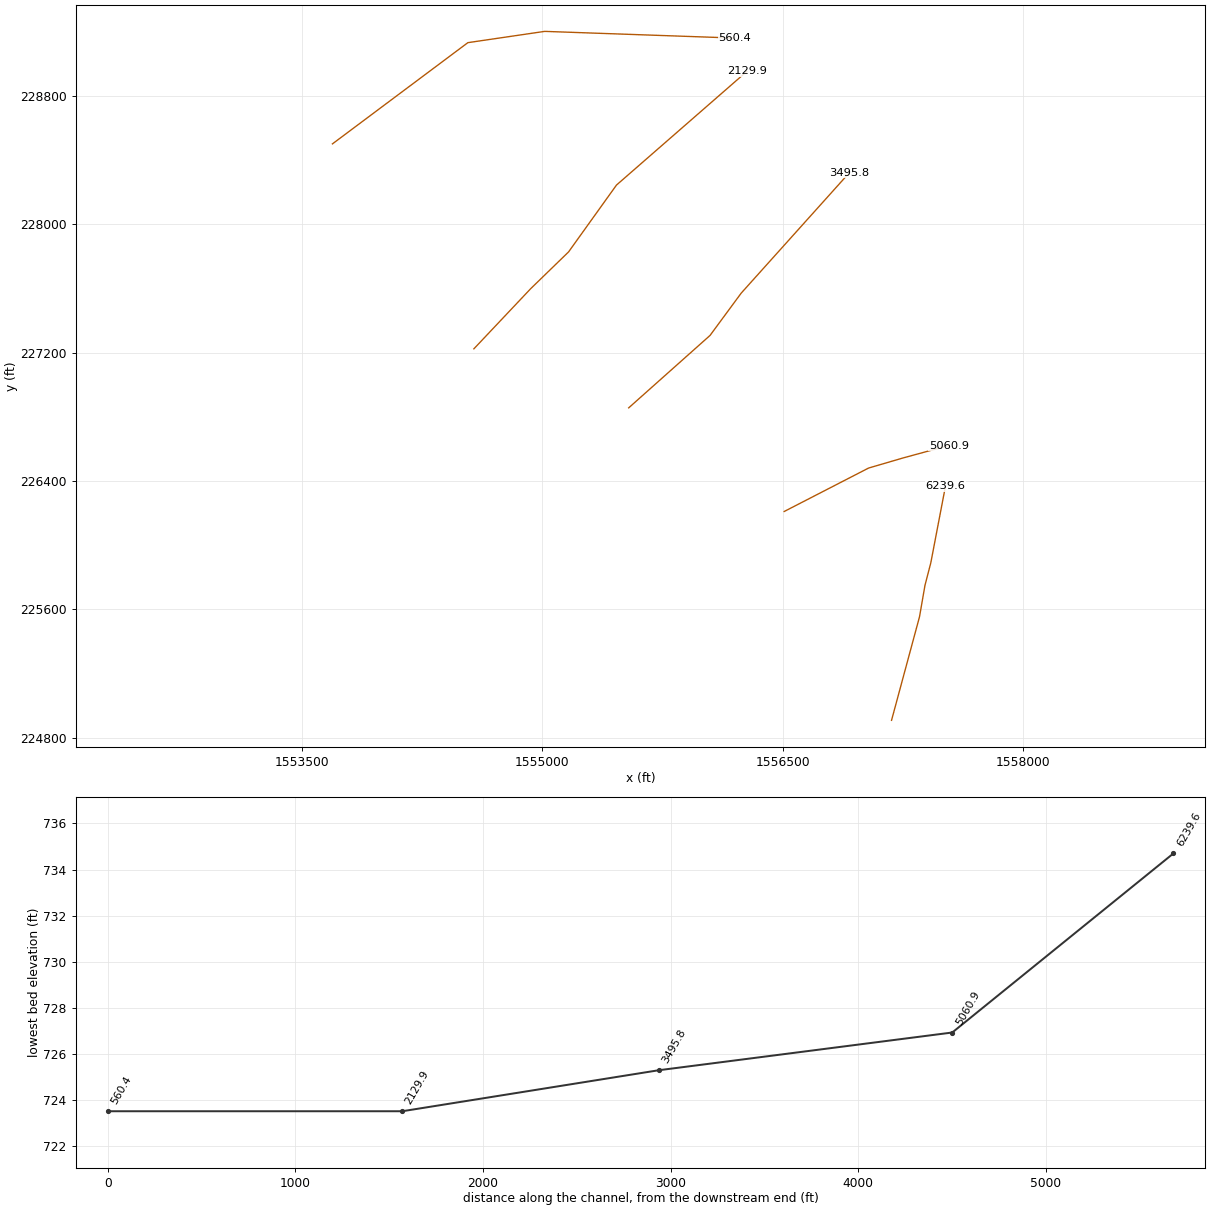
HEC-RAS study BNCR.prj: BNCR

--- BNCR.g01 (geometry) --- (continued)

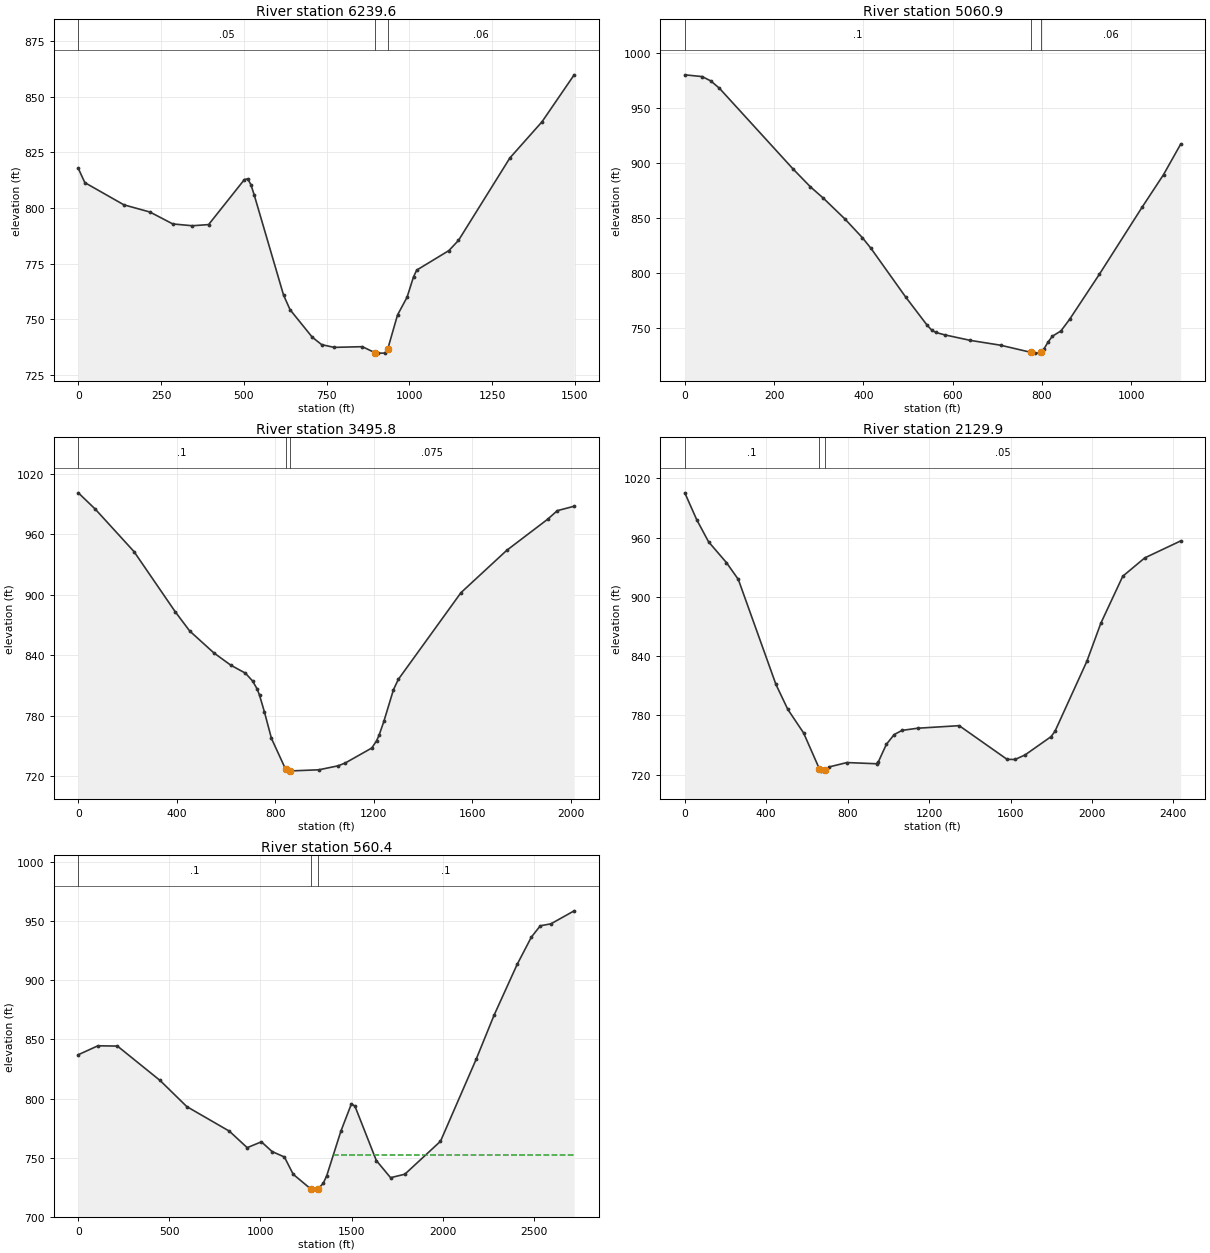
Type RM Length L Ch R = 1 ,6239.6  ,1202.6,1178.7,1154.1
XS GIS Cut Line= 5
     1557178.733      224908.147     1557353.212       225553.98
     1557387.066      225749.293     1557423.524      225889.918
      1557514.67       226366.48
#Sta/Elev= 30
       0  817.74    19.7  811.36   137.7  801.38   216.4  798.14   285.3  792.79
   344.3  791.98   393.5   792.5   501.7  812.76   511.6  813.07   521.4  810.42
   531.2  805.86   619.8  760.85   639.5  754.24   706.7  741.85   735.1  738.51
   772.8  737.29   857.8   737.6   896.3  734.88     906   734.7   925.3   734.7
     935  736.75   964.1  751.84   993.1  759.88  1012.5  769.02  1022.2  772.04
  1119.2   780.8  1148.3  785.39  1303.6  822.47  1400.6  838.73  1497.7  859.84
#Mann= 3 , 0 , 0
       0     .05       0   896.3     .04       0     935     .06       0
Bank Sta=896.3,935
XS Rating Curve= 0 ,0
Exp/Cntr=0.3,0.1

Type RM Length L Ch R = 1 ,5060.9  ,1549.1,1565.1,1580
XS GIS Cut Line= 4
     1556509.462       226210.23     1557035.503      226481.064
     1557249.045      226543.564     1557535.503      226621.689
#Sta/Elev= 30
       0  980.44    38.8  978.84    58.2  974.91    77.6   968.2   242.5  894.73
   281.3  878.48   310.4  868.11   358.9   849.1   397.7   832.2   417.1  822.44
   494.7  778.17   543.2  752.29   552.9  748.05   562.6  745.74     582  743.61
     640  738.52   707.8  734.11   775.3  727.66   785.2  726.92   794.8  727.12
  798.17728.2943   804.5   730.5   814.2   737.1   823.8  742.34   842.9  747.14
   862.1  757.59   929.1  798.82  1024.9  859.93  1072.8  889.53  1111.1  917.24
#Mann= 3 , 0 , 0
       0      .1       0   775.3    .045       0  798.17     .06       0
Bank Sta=775.3,798.17
XS Rating Curve= 0 ,0
Exp/Cntr=0.3,0.1

Type RM Length L Ch R = 1 ,3495.8  ,1368.6,1365.9,1361.5
XS GIS Cut Line= 4
     1555540.053      226856.498     1556046.998      227307.887
     1556241.442      227571.775     1556915.053      228321.775
#Sta/Elev= 30
       0 1001.06    68.9  984.89   226.3  942.82   393.5   883.3   452.5  864.16
   550.9   842.4   619.8  830.23   678.8  822.38   707.7  814.71     727  806.57
   736.6  800.24   755.9  784.16   784.8  757.65   842.1  727.25   852.3  725.28
     862  725.47   977.6  726.61  1055.5  730.54  1084.9  733.39  1192.5   748.2
  1212.1   755.5  1221.9   760.8  1241.5   774.6  1280.6  806.06  1300.2  816.19
  1554.7  902.11  1740.6  944.05    1907  974.89  1946.2  983.39  2014.7  987.77
#Mann= 3 , 0 , 0
       0      .1       0   842.1    .045       0     862    .075       0
Bank Sta=842.1,862
XS Rating Curve= 0 ,0
Exp/Cntr=0.3,0.1

Type RM Length L Ch R = 1 ,2129.9  ,1583.3,1569.5,1555.4
XS GIS Cut Line= 5
     1554574.776      227224.553     1554928.942      227599.553
     1555165.053       227828.72     1555463.665      228245.387
     1556276.165       228953.72
#Sta/Elev= 30
       0 1005.41    58.4  978.26   116.8  955.78   204.4  934.78   262.8  917.74
   447.7  811.31   506.1  786.01   583.6  762.17     661   725.8   670.6   723.5
     690  724.41   709.4  727.78   796.5  732.19   941.6  730.97   951.2  733.13
   989.9   750.6  1028.6  760.56  1067.3   764.8  1144.7  766.98  1347.8  769.55
  1582.8  735.47    1622  735.29    1671  739.87  1798.4  758.34    1818  763.75
  1974.8  834.72  2043.4  873.28  2151.2  920.92    2259  939.48  2435.4  956.68
#Mann= 3 , 0 , 0
       0      .1       0     661    .045       0     690     .05       0
#XS Ineff= 2 , 0
                          994.98          749.75
Permanent Ineff=
       F       F
Bank Sta=661,690
XS Rating Curve= 0 ,0
Exp/Cntr=0.3,0.1

Type RM Length L Ch R = 1 ,560.4   ,537.6,560.4,583.3
XS GIS Cut Line= 4
     1553692.831      228502.331      1554537.16      229133.407
     1555016.327       229203.72     1556199.776      229162.053
#Sta/Elev= 30
       0  837.14   107.4  844.66   214.7  844.43     449  815.34   595.4  793.29
   829.6  772.46   927.2  758.55  1005.3   763.5  1063.8  755.29  1131.6  750.65
    1180  736.03  1276.9  723.59  1286.6   723.5  1315.6  723.69  1344.7  728.34
  1364.1   734.9  1441.6  772.45  1499.7  795.68    1519  793.58  1636.3  747.69
  1714.6  733.16  1792.9  736.12  1988.6  763.95  2184.3  833.22  2282.2  870.31
  2409.4  913.41  2487.7  936.56  2536.6  946.11  2595.4   947.8  2722.6  958.76
#Mann= 3 , 0 , 0
       0      .1       0  1276.9    .045       0  1315.6      .1       0
#XS Ineff= 2 , 0
                         1399.67          752.21
Permanent Ineff=
       F       F
Bank Sta=1276.9,1315.6
XS Rating Curve= 0 ,0
Exp/Cntr=0.3,0.1

Chan Stop Cuts=-1
Use User Specified Reach Order=0
Composite Channel Slope=5